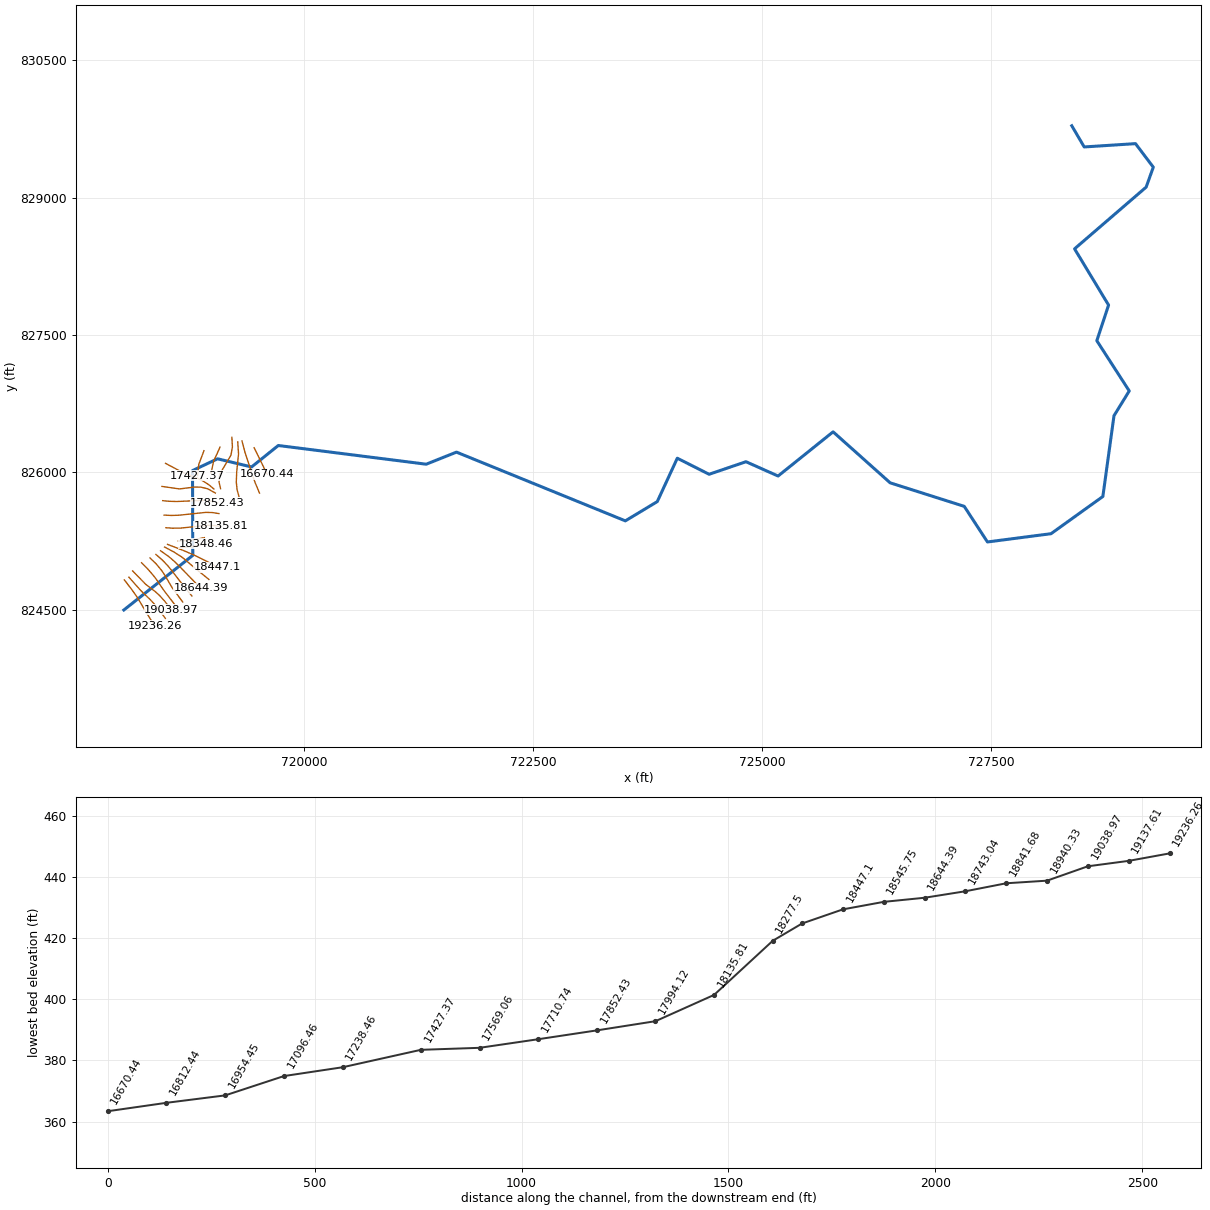
--- 14876_ras.prj (project) ---

Proj Title=14876
Current Plan=p01
Default Exp/Contr=0.3,0.1
English Units
Geom File=g01
Flow File=f01
Plan File=p01
Y Axis Title=Elevation
X Axis Title(PF)=Main Channel Distance
X Axis Title(XS)=Station
BEGIN DESCRIPTION:
RFD model 14876 exported to HEC-RAS
END DESCRIPTION:

--- 14876_ras.p01 (plan) ---

Plan Title=Plan 01
Program Version=4.10
Short Identifier=Plan 01
Geom File=g01
Flow File=f01
Subcritical Flow
Calc Critical at every XS
Secant Critical Depth

--- 14876_ras.f01 (steady flow) ---

Flow Title=Flow 01
Program Version=5.01
Number of Profiles= 6
Profile Names=10yr,25yr,50yr,100yr,100plus,500yr
River Rch & RM=14876,80,19236.26
 2920.67 4725.58 6442.13 8003.5811685.2313625.17
River Rch & RM=14876,80,19137.61
 2922.65 4728.91 6446.78 8009.4711693.8313634.23
River Rch & RM=14876,80,19038.97
 2927.26 4736.63 6457.54 8023.0911713.7113655.05
River Rch & RM=14876,80,18841.68
  2945.4 4767.02 6499.95  8076.811792.1313737.32
River Rch & RM=14876,80,18743.04
 2947.16 4769.98 6504.09 8082.0711799.8213745.44
River Rch & RM=14876,80,18644.39
 2948.71 4772.61 6507.77 8086.7511806.6513752.67
River Rch & RM=14876,80,18545.75
 2954.01 4781.53 6520.24 8102.5811829.7613777.03
River Rch & RM=14876,80, 18447.1
 2958.88 4789.74 6531.74 8117.19 11851.113799.57
River Rch & RM=14876,80,18348.46
 2960.63 4792.69 6535.88 8122.4511858.7813807.68
River Rch & RM=14876,80,18135.81
  2961.8 4794.66 6538.64 8125.96 11863.913813.09
River Rch & RM=14876,80,17994.12
 2968.81 4806.48 6555.19 8146.99 11894.613845.51
River Rch & RM=14876,80,17852.43
 2969.59 4807.79 6557.02 8149.3211898.0113849.11
River Rch & RM=14876,80,17710.74
 2978.21  4822.3 6577.32 8175.0811935.6213888.69
River Rch & RM=14876,80,17569.06
 3011.63 4878.74 6656.44 8275.7112082.54 14043.9
River Rch & RM=14876,80,17427.37
 3013.15 4881.31 6660.05 8280.3312089.2814051.06
River Rch & RM=14876,80,17238.46
 3015.99 4886.14 6666.84 8288.9812101.9114064.49
River Rch & RM=14876,80,17096.46
 3018.46 4890.32 6672.72 8296.4812112.8614076.11
River Rch & RM=14876,80,16954.45
 3019.22 4891.61 6674.54 8298.7912116.2414079.69
River Rch & RM=14876,80,16812.44
  3021.7 4895.82 6680.44 8306.3112127.2214091.32
River Rch & RM=14876,80,16670.44
 3025.15 4901.65 6688.62 8316.7312142.4314107.41
River Rch & RM=14876,80, 16390.5
 3027.04 4904.87 6693.14  8322.512150.8514116.34
River Rch & RM=14876,80, 16185.6
 3272.32 5318.53 7272.62 9059.0713226.2415241.65
River Rch & RM=14876,80, 15980.7
 3276.25 5325.19 7281.98 9070.9913243.6415259.85
River Rch & RM=14876,80,15775.79
 3284.36 5338.89  7301.2 9095.4513279.3615297.09
River Rch & RM=14876,80,15637.27
 3288.28 5345.53 7310.53 9107.3413296.7215315.26
River Rch & RM=14876,80,15436.37
 3491.01 5682.95 7779.43 9699.0914160.6716193.23
River Rch & RM=14876,80,15198.36
 3498.19 5695.13 7796.54  9720.914192.5116226.23
River Rch & RM=14876,80,14960.35
 3503.19 5703.59 7808.42 9736.0214214.5916249.06
River Rch & RM=14876,80,14722.34
 3511.51 5717.66 7828.19  9761.214251.3616287.08
River Rch & RM=14876,80,14246.33
 3527.99 5745.54 7867.31 9811.0114324.0816362.18
River Rch & RM=14876,80,14008.32
 3589.18 5848.46  8011.3  9993.814590.9416635.29
River Rch & RM=14876,80,13770.31
 3592.85 5854.68 8020.0310004.93 14607.216652.04
River Rch & RM=14876,80,13532.31
 3730.95 6087.31 8345.7710418.77 15211.417268.83
River Rch & RM=14876,80, 13294.3
 3735.87 6095.64 8357.4710433.6715233.1517291.11
River Rch & RM=14876,80,13078.03
 3746.64 6113.85 8383.0410466.23 15280.717339.76
River Rch & RM=14876,80,12861.76
 3748.65 6117.25 8387.81 10472.315289.5617348.82
River Rch & RM=14876,80,12645.49
 3767.73 6149.38 8432.7910529.4415372.99 17433.6
River Rch & RM=14876,80,12429.22
 3777.64 6166.11 8456.2510559.2815416.5417477.99
River Rch & RM=14876,80,12344.69
 3778.55 6167.65 8458.4110562.0315420.5617482.09
River Rch & RM=14876,80,12100.29
 3783.29 6175.66 8469.6610576.3515441.4717503.45
River Rch & RM=14876,80,11855.88
 3795.37 6196.07 8498.2810612.7615494.64 17557.6
River Rch & RM=14876,80,11409.78
 3803.18 6209.28 8516.84 10636.415529.1517592.85
River Rch & RM=14876,80,10858.87
 3833.78  6261.1 8589.6310729.1415664.5417731.11
River Rch & RM=14876,80,10145.05
 3922.46 6411.54 8801.2510999.0716058.6418133.68
River Rch & RM=14876,80,9900.645
 5294.76 8651.9111877.3114836.9821661.9923418.03
River Rch & RM=14876,80, 9656.24
 5299.79 8660.4511889.3514852.3521684.4323439.99
River Rch & RM=14876,80,9411.835
 5304.09 8667.7911899.7114865.5921703.7723459.02
River Rch & RM=14876,80,9167.431
  5312.5 8682.2411920.1914891.8821742.1523497.06
River Rch & RM=14876,80,8923.026
 5315.41 8687.2311927.2714900.9721755.4123510.23
River Rch & RM=14876,80,8678.622
 5321.93 8698.4111943.0914921.2421785.0123539.47
River Rch & RM=14876,80,8434.217
 5336.44 8723.3411978.4514966.65 21851.323605.21
River Rch & RM=14876,80,8189.813
 5339.39 8728.3911985.5814975.7821864.6323618.35
River Rch & RM=14876,80,7945.408
  5358.2 8760.7312031.4615034.7121950.6723703.68
River Rch & RM=14876,80,7701.004
 5361.77 8766.8412040.1215045.8121966.8923719.71
River Rch & RM=14876,80,7456.599
 5366.58 8775.1212051.87 15060.921988.9223741.57
River Rch & RM=14876,80,7212.195
 5368.36 8778.18 12056.215066.4621997.0323749.58
River Rch & RM=14876,80, 6967.79
 5564.39 9107.5312516.8515650.7822850.1424567.78
River Rch & RM=14876,80,6723.386
  5569.2 9115.7912528.5515665.7922872.0524589.34
River Rch & RM=14876,80,6478.981
 5901.33 9677.6213317.7516670.6524339.1425998.99
River Rch & RM=14876,80,6234.577
 5907.19 9687.67   1333216688.9324365.8426024.99
River Rch & RM=14876,80,5990.172
 5910.51 9693.3713340.0816699.2924380.9726039.74
River Rch & RM=14876,80,5501.363
  5925.5 9719.1913376.7516746.4424449.8126107.14
River Rch & RM=14876,80,5256.959
 5928.57 9724.5113384.3216756.2124464.0726121.18
River Rch & RM=14876,80, 4768.15
 5982.13 9816.9513515.8116925.4524711.1626363.48
River Rch & RM=14876,80,4523.745
 5985.95 9823.5713525.2416937.6224728.9326380.95
River Rch & RM=14876,80,4279.341
  5991.6 9833.36 13539.216955.62 24755.2 26406.8
River Rch & RM=14876,80,4034.936
 5994.98  9839.213547.5116966.3324770.8426422.17
River Rch & RM=14876,80,3790.532
 6024.84  9890.813620.94 17060.924908.9126557.53
River Rch & RM=14876,80,3633.679
 6026.06 9892.9113623.9517064.7824914.58 26563.1
River Rch & RM=14876,80,  3389.5
 6026.82 9894.2313625.8317067.2124918.1226566.59
River Rch & RM=14876,80,3145.321
  6032.3 9903.7313639.3817084.6824943.6426591.67
River Rch & RM=14876,80,2656.962
 6041.02 9918.8213660.8717112.3824984.0826631.37
River Rch & RM=14876,80,2168.604
 6046.68 9928.6113674.8217130.3625010.3226657.13
River Rch & RM=14876,80,1680.246
 6105.3810030.2413819.6317317.0625282.9126924.56
River Rch & RM=14876,80,870.3143
 6131.3510075.1513883.5817399.4625403.2227042.31
River Rch & RM=14876,80,432.5782
 6135.1710081.7513892.9817411.58 25420.927059.62
River Rch & RM=14876,80,140.2603
 6180.2110159.4614003.49 17553.825628.5527262.04
Boundary for River Rch & Prof#=14876,80,1
Up Type= 0
Dn Type= 2
Boundary for River Rch & Prof#=14876,80,2
Up Type= 0
Dn Type= 2
Boundary for River Rch & Prof#=14876,80,2
Up Type= 0
Dn Type= 2
Boundary for River Rch & Prof#=14876,80,2
Up Type= 0
Dn Type= 2
Boundary for River Rch & Prof#=14876,80,2
Up Type= 0
Dn Type= 2
Boundary for River Rch & Prof#=14876,80,2
Up Type= 0
Dn Type= 2

--- 14876_ras.g01 (geometry) ---

Geom Title=14876
Program Version=4.10

River Reach=14876,80
Reach XY= 30
718028.472963333824498.193108335718781.154143035825094.751792163
718778.332812786826020.793342054719051.770263314826149.265482366
719423.438241184826060.172274962 719715.10490784826294.547274932
721330.347662807826090.279088229721661.145581752826222.182468057
723505.035463333825471.630608305723853.993796676825681.700052798
724072.743796676826155.658386067724419.966018885825980.311163843
724822.743796736826117.463941634725173.438241154825961.213941634
725774.132685602826443.852830574726397.396574497825886.908386081
727206.424352229825629.963941649727459.896574557825241.075052723
728154.341018945825331.352830514728720.313241154825737.602830514
728841.841018915826619.547274932729008.507685572 826890.38060829
728654.341018885827438.991719514728782.813241154827827.880608305
728411.285463363828442.463941634729192.805008948829115.880000934
729271.245773941 829333.94532755729076.712676793829591.231036648
728516.645614892829555.148284748 728380.89534681829786.395317925

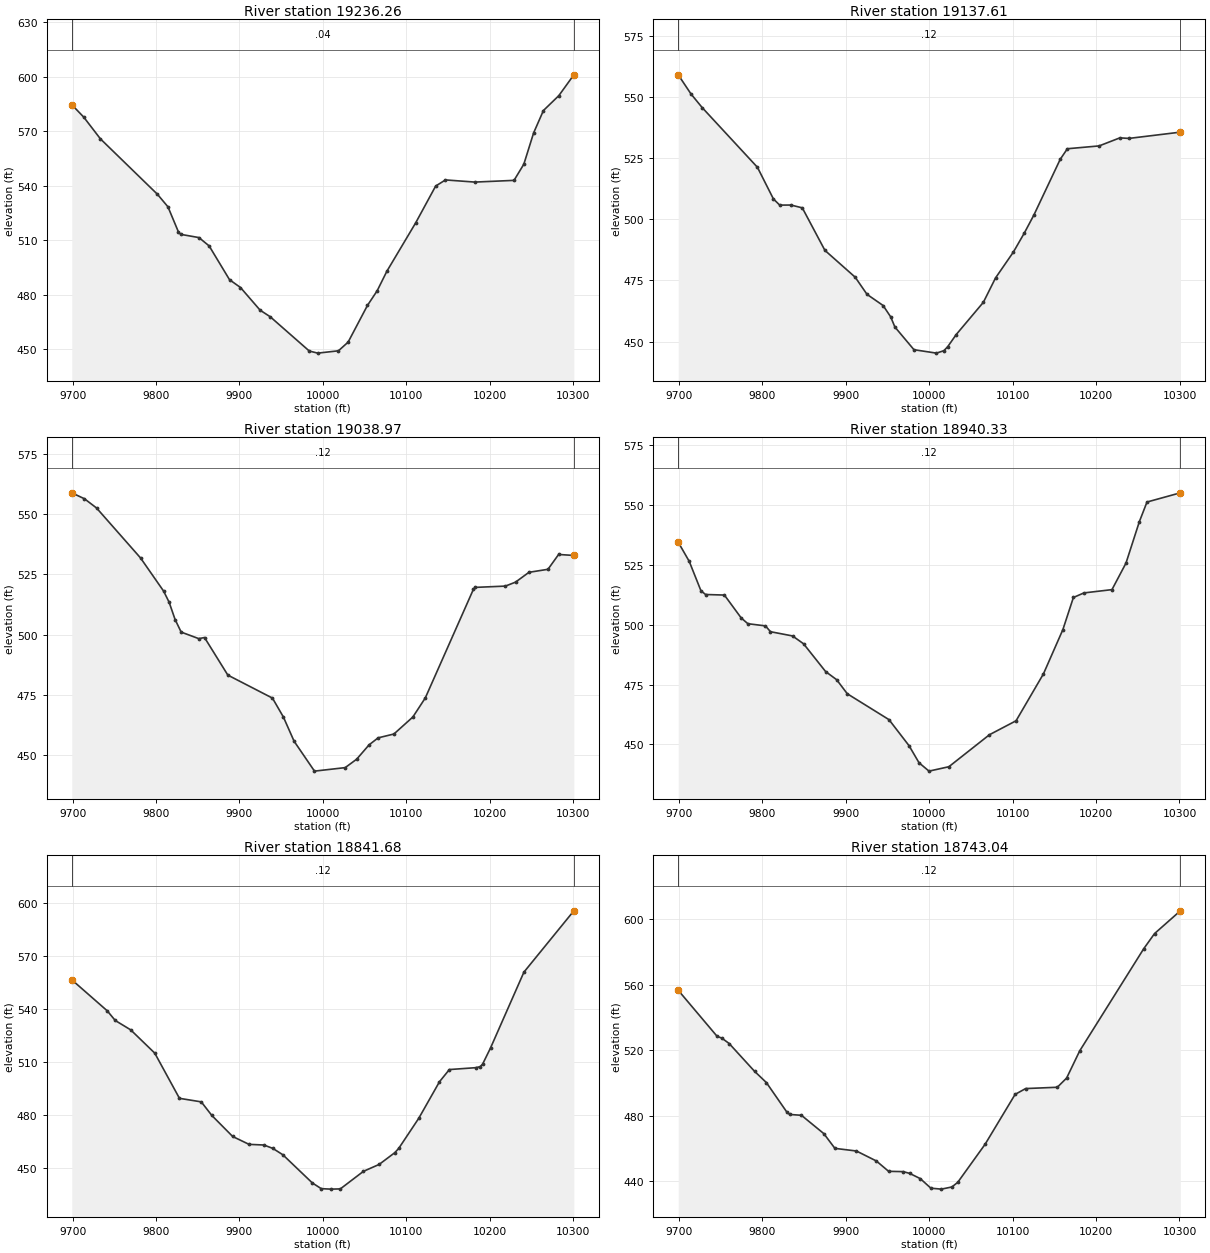
Type RM Length L Ch R = 1 ,19236.26,98.644400,98.644400,98.644400
XS GIS Cut Line= 6
718034.058713815824826.349350867718113.814830527824722.800590902
718173.663661262824637.738118977718207.644154985824582.030344434
718256.229343173824499.601924025718364.432994487824323.941652294
#Sta/Elev= 30
9699.036584.68159713.361577.83249733.354565.85159801.718535.29329814.341528.3753
9826.963514.47769829.739513.18759851.504511.41469863.731506.81889888.186488.1838
9901.312483.89149924.867471.38389936.954467.76819983.808448.87199993.922447.7136
10018.75 448.99610030.36453.771710053.58 474.04510065.19482.0905 10076.8 492.836
10111.41  519.5710135.32 539.81510147.07543.2003 10182.3542.007310229.28542.9539
10241.03551.876810252.77569.117410264.52581.460410283.01589.674810300.99601.1375
#Mann= 3 , 0 , 0
9699.036    0.04       09699.036    0.04       010300.99    0.04       0
#XS Ineff= 2 , 0
       0                               0
Bank Sta=9699.036,10300.99
Exp/Cntr=0.3,0.1

Type RM Length L Ch R = 1 ,19137.61,98.644400,98.644400,98.644400
XS GIS Cut Line= 6
718083.323217871824856.589047156718212.809973837824710.966917847
718316.509829523824611.266121069718356.625541107824568.488233382
718413.981497235824498.419163018718481.361222236824406.508451181
#Sta/Elev= 30
9699.016558.98239714.387551.12999727.651545.62069793.968521.20359813.134508.2711
9820.657505.75589834.211505.77859847.766504.62969874.875487.25749911.172476.2948
9925.344 469.2929944.653 464.7249953.689460.11069958.766455.94259981.623446.6724
10008.56445.274710017.52446.274910022.15447.930710032.28452.867410064.83466.0403
10079.44476.008610100.95486.641910113.87494.306410125.45 501.72910157.02524.4958
10165.56528.782510203.63 529.93810228.43533.223810239.45533.008910300.95  535.56
#Mann= 3 , 0 , 0
9699.016    0.12       09699.016    0.12       010300.95    0.12       0
#XS Ineff= 2 , 0
       0                               0
Bank Sta=9699.016,10300.95
Exp/Cntr=0.3,0.1

Type RM Length L Ch R = 1 ,19038.97,98.644300,98.644300,98.644300
XS GIS Cut Line= 6
718124.514999921824924.679991228718267.400199614824778.517408949
718373.925724487824696.867815493718416.941910389824657.794443044
718472.843744327824596.053483692718548.435790356824500.686070733
#Sta/Elev= 30
9699.044558.74759714.243556.29259728.739552.4727 9781.48531.78099809.106518.0656
9815.714513.47719822.919506.27259830.194501.07429851.286498.37079858.164498.8303
9886.133483.2641 9939.63473.7427 9952.73465.90659965.582 455.8689990.005443.5023
10026.81 444.951 10040.6448.453110055.47454.392810066.29457.280310085.21458.8712
10107.94465.918910122.84473.814510180.56518.826910182.69519.589310218.85520.1231
10230.99521.762410247.09525.832610269.89527.076910282.65533.222710300.91532.8152
#Mann= 3 , 0 , 0
9699.044    0.12       09699.044    0.12       010300.91    0.12       0
#XS Ineff= 2 , 0
       0                               0
Bank Sta=9699.044,10300.91
Exp/Cntr=0.3,0.1

Type RM Length L Ch R = 1 ,18940.33,98.644400,98.644400,98.644400
XS GIS Cut Line= 6
718221.956347508825014.375674742718288.828331825824946.691558367
718354.029273606824871.264909582 718390.34403017824822.842727338
718460.322231367824718.639453773 718594.88904013 824543.30403594
#Sta/Elev= 30
9699.051534.51979712.231526.50289726.289514.20349731.839 512.6489754.404512.4157
9774.523502.85079782.519500.44039803.636499.52359809.653497.0912 9836.09495.3215
9849.308492.04139875.745480.42889888.963477.02639901.731471.1467 9951.73460.3209
9975.789449.42449987.761442.27719999.723438.7978 10023.5440.635510072.18454.0183
10104.08459.852210136.93 479.48610160.19497.9585 10172.8511.3951 10185.4513.3094
10219.05514.683310235.83525.7569 10251.9 543.11610261.04551.315110300.99555.1605
#Mann= 3 , 0 , 0
9699.051    0.12       09699.051    0.12       010300.99    0.12       0
#XS Ineff= 2 , 0
       0                               0
Bank Sta=9699.051,10300.99
Exp/Cntr=0.3,0.1

Type RM Length L Ch R = 1 ,18841.68,98.644400,98.644400,98.644400
XS GIS Cut Line= 6
718313.918805645825066.841336239 718382.13700902825000.545274448
718439.252746625824932.070414821718476.487842715824876.890634833
  718555.2971348824742.639658842718671.239038993 824585.53163934
#Sta/Elev= 30
9699.047556.68059741.499539.11059751.187533.59339769.665528.28669798.547515.0778
9828.154489.44469854.303487.43519866.994479.71569891.933467.80759911.555463.3362
9929.433 462.9629940.188461.02279952.145457.41569987.472441.44389998.139438.2092
10009.57437.941510021.02438.070110048.74448.040910067.54451.948810086.33458.6152
10091.09461.082810115.04478.1169 10139.9498.856910151.73505.765610183.47506.8305
10188.57507.396910191.57 508.82710201.13518.047810241.12561.020210300.98595.7961
#Mann= 3 , 0 , 0
9699.047    0.12       09699.047    0.12       010300.98    0.12       0
#XS Ineff= 2 , 0
       0                               0
Bank Sta=9699.047,10300.98
Exp/Cntr=0.3,0.1

Type RM Length L Ch R = 1 ,18743.04,98.644400,98.644400,98.644400
XS GIS Cut Line= 6
718378.256938133825104.782916629718450.160013639825042.503552387
 718511.42360005824977.698789258718550.401577409824929.895279968
718675.951400902824767.370295466 718771.69184534824651.177122109
#Sta/Elev= 30
9699.023556.5672 9745.71528.44629751.162527.4489 9760.09524.11139790.475507.2001
9804.712500.30079829.561482.06999832.794480.85979846.758480.34299873.587469.1656
9886.863460.18589912.668458.57399936.513452.50729951.258446.18979968.866 445.993
9976.578  444.919989.239441.730410001.94435.898310014.56435.330310027.19436.6532
10034.18439.504610066.95462.691810102.93493.106910115.55496.6441 10153.5497.4432
10164.66503.033410180.39519.646610257.16581.939510270.12591.152310300.99605.0202
#Mann= 3 , 0 , 0
9699.023    0.12       09699.023    0.12       010300.99    0.12       0
#XS Ineff= 2 , 0
       0                               0
Bank Sta=9699.023,10300.99
Exp/Cntr=0.3,0.1

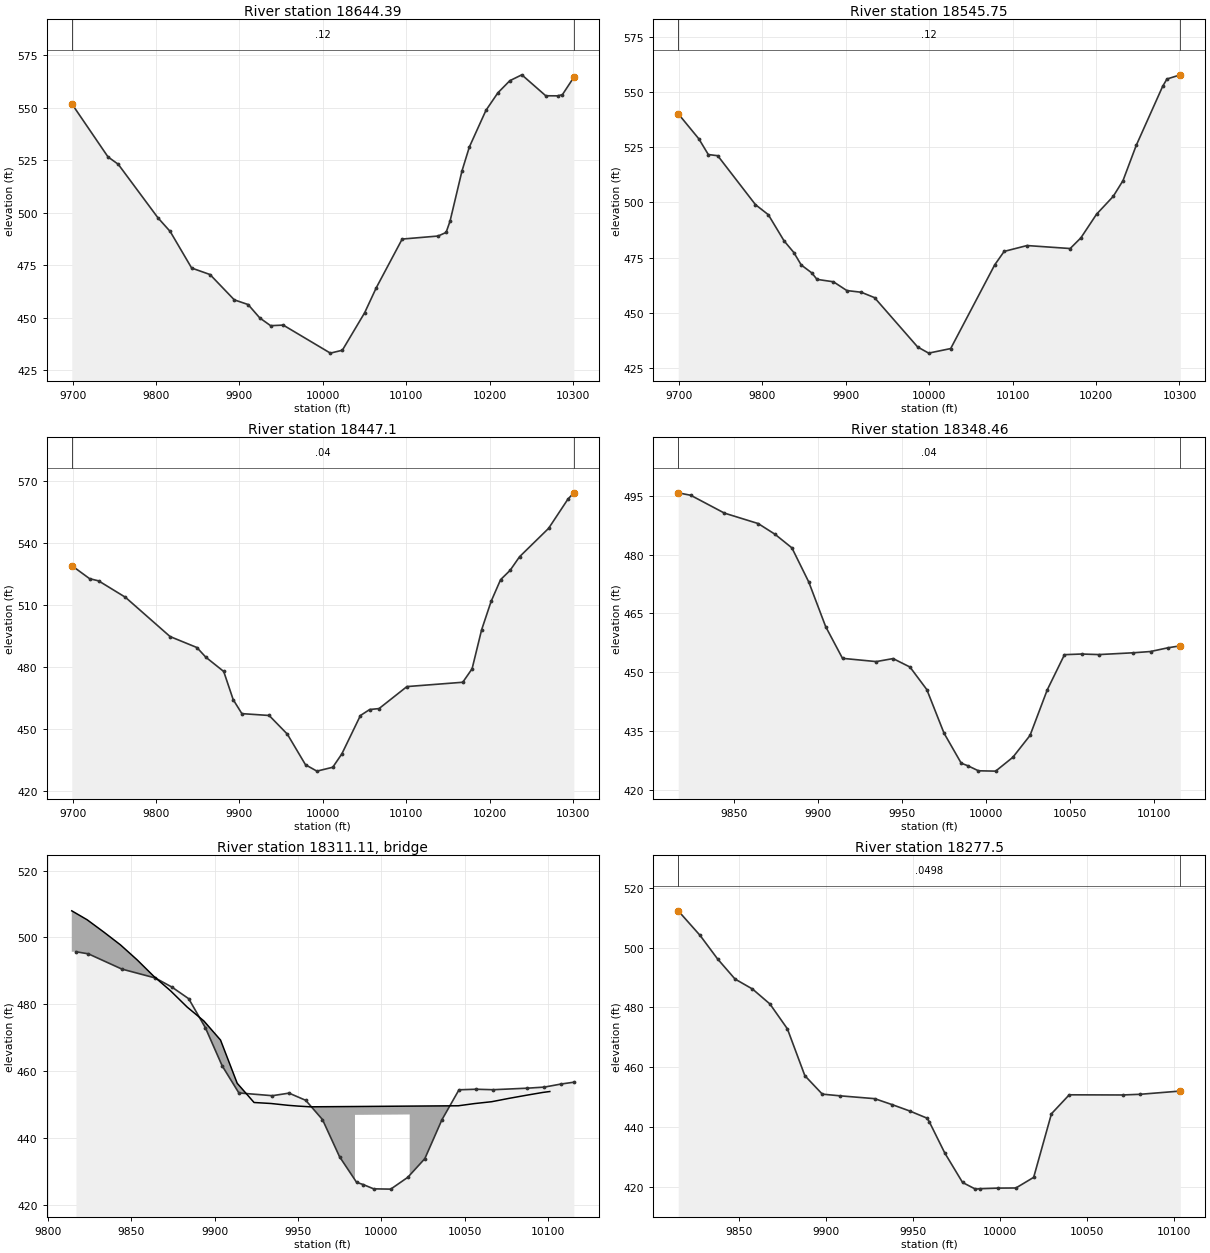
Type RM Length L Ch R = 1 ,18644.39,98.644400,98.644400,98.644400
XS GIS Cut Line= 6
718429.465834309825144.946958633718507.231472187825090.142740956
718546.813314655825058.084317309718583.199168921825025.594585687
718652.854801676824956.917972634718868.471788528824735.181363022
#Sta/Elev= 30
 9699.04551.83569742.512 526.5269754.745523.04479802.348497.57439817.042491.0645
9842.779473.67699864.757470.59679893.893458.54969910.465456.31789924.508449.9265
 9937.47446.25829952.594446.540110009.09433.208110023.44434.580410050.21452.4269
10064.16464.340510095.17487.461210138.21488.902910147.84490.610610152.55495.9736
 10166.9519.888910175.73531.262710195.59548.673210209.94557.032610224.29562.8029
10238.63 565.57810267.32555.616610281.67555.5823 10287.3556.1555   10301564.4306
#Mann= 3 , 0 , 0
 9699.04    0.12       0 9699.04    0.12       0   10301    0.12       0
#XS Ineff= 2 , 0
       0                               0
Bank Sta=9699.04,10301
Exp/Cntr=0.3,0.1

Type RM Length L Ch R = 1 ,18545.75,98.644300,98.644300,98.644300
XS GIS Cut Line= 6
718473.145035919825185.511950649 718573.70152119825132.300292456
718657.399259404825078.869241746718694.046067619825050.510317636
 718789.39039361824968.502428532718957.431717101 824831.58724027
#Sta/Elev= 30
9699.036540.08239723.762528.74389735.076521.6536 9746.39 521.1199791.645498.9836
9807.031494.45629825.973482.59499837.629477.35449846.477471.7291 9859.11468.1505
9865.389465.21479885.124464.11499901.169460.1543 9918.46459.39019934.393456.9516
9986.101434.63779999.288431.862410025.69433.927910078.45471.756710089.78477.8578
10117.27480.503210168.94479.155410181.77483.9807 10200.6494.695310220.46502.6891
10232.26509.8548 10248.1525.759110279.76552.439410284.96555.800310300.99557.6923
#Mann= 3 , 0 , 0
9699.036    0.12       09699.036    0.12       010300.99    0.12       0
#XS Ineff= 2 , 0
       0                               0
Bank Sta=9699.036,10300.99
Exp/Cntr=0.3,0.1

Type RM Length L Ch R = 1 , 18447.1,98.644400,98.644400,98.644400
XS GIS Cut Line= 6
718505.014678061825214.941376176718677.052876182825148.647170346
718805.928094639825092.825332108 718943.58486648825024.838672823
718994.855295073824996.916369015719051.089640024824963.857658422
#Sta/Elev= 30
9699.016529.13179720.434522.7909 9731.15521.74219763.301513.78189816.884494.7092
9849.035489.38979859.752484.69319881.185477.77919892.539 464.1239902.953457.3108
9935.661456.41249957.467447.35839979.273432.48859992.928429.409410011.93431.2899
10022.82437.7733 10045.1456.401210056.26459.314510067.41459.756710100.87470.4391
10167.79472.534810178.97 479.05610190.36497.923510201.75511.745710213.13522.3072
10224.52526.827610235.91 533.45110270.71547.216910293.91 561.41410300.98564.4563
#Mann= 3 , 0 , 0
9699.016    0.04       09699.016    0.04       010300.98    0.04       0
#XS Ineff= 2 , 0
       0                               0
Bank Sta=9699.016,10300.98
Exp/Cntr=0.3,0.1

Type RM Length L Ch R = 1 ,18348.46,70.957500,70.957500,70.957500
XS GIS Cut Line= 3
718627.591223776  825178.5267369718775.104159445825189.855270177
718922.326381683825221.799714625
#Sta/Elev= 28
9816.916495.72729824.347495.10189844.406490.55259864.465487.89429874.494485.1567
9884.524481.69439894.553472.99079904.583461.63849914.612453.53699934.671452.7112
  9944.7453.4777 9954.73451.32439964.759445.5661 9974.99434.46679985.223426.8127
9989.126426.16539995.455424.875810005.69424.789810015.92 428.31910026.15433.9017
10036.39445.516310046.62454.473810056.85454.640610067.08454.498510087.55454.9565
10097.78455.277310108.01456.213210115.51456.7397
#Mann= 3 , 0 , 0
9816.916    0.04       09816.916    0.04       010115.51    0.04       0
#XS Ineff= 2 , 0
       0                               0
Bank Sta=9816.916,10115.51
Exp/Cntr=0.3,0.1

Type RM Length L Ch R = 3 ,18311.11,,,
BEGIN DESCRIPTION:
END DESCRIPTION:
Bridge Culvert--1,0,-1,-1, 0
Deck Dist Width WeirC Skew NumUp NumDn MinLoCord MaxHiCord MaxSubmerge Is_Ogee
23.503700,23.950100,2.6,0, 30, 30, , , 0.95, 0, 0,0,,
 9814.39 9823.61 9833.61 9843.61 9853.61 9863.61 9873.61 9883.61 9893.61 9903.61
 9913.61 9917.59 9923.72 9933.91 9944.09 9950.25 9954.27 9957.16 9984.25 9984.25
10017.0610017.0610046.2410056.1010056.3710066.2810076.4610086.6410096.8310101.09
  507.96  505.29  501.61  497.78  493.30  488.38  484.07  479.19  475.05  469.34
  456.42  454.16  450.68  450.38  449.84  449.60  449.48  449.39  449.48  449.48
  449.60  449.60  449.70  450.37  450.38  450.92  451.90  452.81  453.68  453.96
 -492.04 -494.71 -498.39 -502.22 -506.70 -511.62 -515.93 -520.81 -524.95 -530.66
 -543.58 -545.84 -549.32 -549.62 -550.16 -550.40 -550.52 -550.61 -550.52  446.98
  447.10 -550.40 -550.30 -549.63 -549.62 -549.08 -548.10 -547.19 -546.32 -546.04
 9814.39 9823.61 9833.61 9843.61 9853.61 9863.61 9873.61 9883.61 9893.61 9903.61
 9913.61 9917.59 9923.72 9933.91 9944.09 9950.25 9954.27 9957.16 9975.86 9975.86
10008.6710008.6710046.2410056.1010056.3710066.2810076.4610086.6410096.8310101.09
  507.96  505.29  501.61  497.78  493.30  488.38  484.07  479.19  475.05  469.34
  456.42  454.16  450.68  450.38  449.84  449.60  449.48  449.39  449.45  449.45
  449.57  449.57  449.70  450.37  450.38  450.92  451.90  452.81  453.68  453.96
 -492.04 -494.71 -498.39 -502.22 -506.70 -511.62 -515.93 -520.81 -524.95 -530.66
 -543.58 -545.84 -549.32 -549.62 -550.16 -550.40 -550.52 -550.61 -550.55  446.95
  447.07 -550.43 -550.30 -549.63 -549.62 -549.08 -548.10 -547.19 -546.32 -546.04
BR Coef=-1 , 0 , 0 ,, 0 ,,,0.8,0,1,0,
WSPro=,,,, 1 ,,,, 0 ,,,, 0 ,,,,-1 ,-1 ,-1 , 0 , 0 , 0 , 0 , 0
BC Design=,, 0 ,, 0 ,,,,,,

Type RM Length L Ch R = 1 , 18277.5,141.689200,141.689200,141.689200
XS GIS Cut Line= 4
718622.479159445825251.461751655718766.229159445825259.795084998
718843.312492758 825275.21175167718907.479159474825288.128418326
#Sta/Elev= 27
9815.388512.3139 9827.93504.07359837.947496.22219847.964 489.4799857.981486.1347
9867.997481.11979878.014472.80059888.031457.11629898.048450.93239908.065450.3775
9928.098449.41979938.115447.42039948.132445.30649958.149442.8873 9959.38441.7367
9968.324431.21219978.522421.3537 9985.92419.1279 9988.72 419.2679998.918419.4677
10009.12419.511410019.31  423.0710029.51444.361810039.71 450.70810070.31450.6536
10080.51450.887210103.44451.9691
#Mann= 3 , 0 , 0
9815.388  0.0498       09815.388  0.0498       010103.44  0.0498       0
#XS Ineff= 2 , 0
       0                               0
Bank Sta=9815.388,10103.44
Exp/Cntr=0.3,0.1

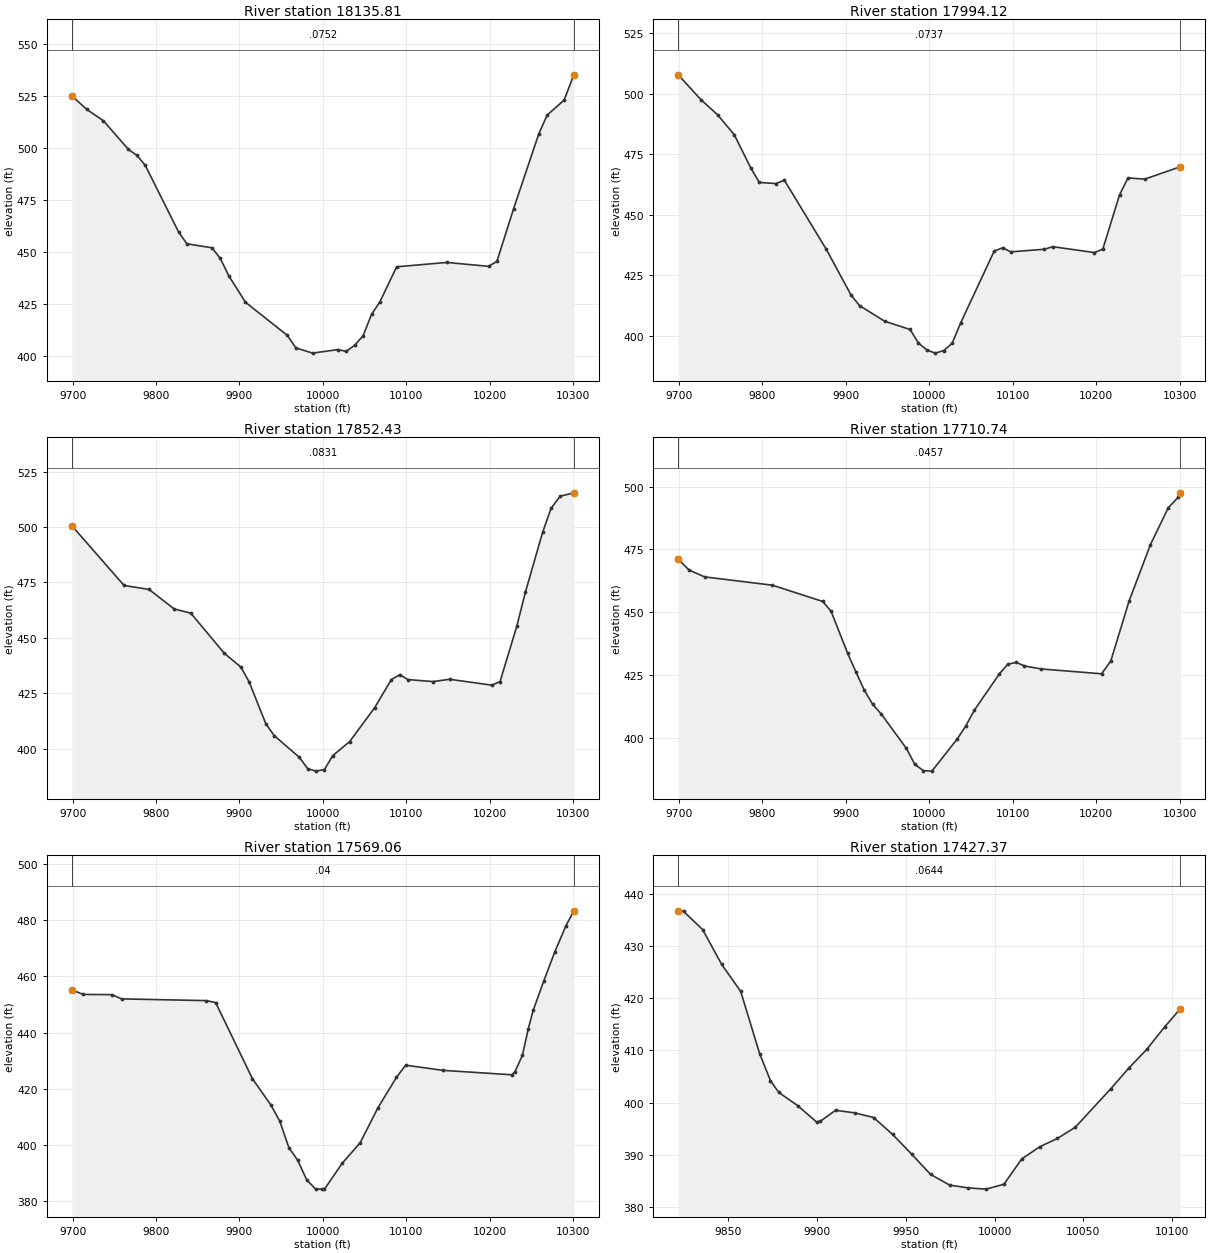
Type RM Length L Ch R = 1 ,18135.81,141.689200,141.689200,141.689200
XS GIS Cut Line= 6
718487.252053324825396.820238633718561.695994847825391.192049093
718647.070968558 825392.49034535718941.214232166825422.484981548
719012.587806483825420.630973967719086.533267093825410.503340025
#Sta/Elev= 30
9699.036525.22419716.835518.68269736.892513.20469766.977 499.3989776.997496.5887
9786.997491.83039827.008459.76739837.015453.99739867.064452.09149877.106446.9562
9887.148438.70369907.232425.91889957.572409.91429967.658403.94979987.828401.4245
10018.07403.133110028.15402.275610038.22405.2276 10048.3409.796110058.37420.0484
10068.45426.107410088.52442.942310148.65445.040810198.67443.160810208.68445.5156
 10228.7470.860310258.89506.856510268.96  515.9110289.23523.082110300.94 535.264
#Mann= 3 , 0 , 0
9699.036  0.0752       09699.036  0.0752       010300.94  0.0752       0
#XS Ineff= 2 , 0
       0                               0
Bank Sta=9699.036,10300.94
Exp/Cntr=0.3,0.1

Type RM Length L Ch R = 1 ,17994.12,141.689100,141.689100,141.689100
XS GIS Cut Line= 6
718467.905525744825534.257377225718547.456508828 825530.47255728
718629.353383536825532.990529015718921.862218121825564.075854222
718993.234068683825562.446328954719066.975210789825551.055958116
#Sta/Elev= 30
 9699.05 507.8329726.175 497.6179746.198491.3205 9766.22483.09349786.238   469.2
9796.243463.38089816.252462.89299826.257464.30289876.342435.84389906.473416.6698
9916.517412.42999946.705405.96929976.968402.59799987.056397.00459997.144394.1046
10007.23392.825510017.31393.8901 10027.4396.888410037.48405.204210077.81435.0193
10087.85436.321210097.87434.684810137.97435.7499   10148436.816510198.03434.3813
10208.03435.809110228.05458.193910238.13465.215710258.29464.729710300.93469.8539
#Mann= 3 , 0 , 0
 9699.05  0.0737       0 9699.05  0.0737       010300.93  0.0737       0
#XS Ineff= 2 , 0
       0                               0
Bank Sta=9699.05,10300.93
Exp/Cntr=0.3,0.1

Type RM Length L Ch R = 1 ,17852.43,141.689200,141.689200,141.689200
XS GIS Cut Line= 6
718452.611553007825692.153344961718525.438071284825685.083941847
718606.378897561825682.928260782718907.767807235825695.600288977
718978.788001407825688.628694838 719050.56482231825668.405660359
#Sta/Elev= 30
9699.037500.64279761.718473.63669791.774471.83459821.785463.01989841.792461.1155
9881.809443.04329901.818436.77639911.823429.98179931.836411.06289941.853405.8235
9971.904396.0305 9981.92390.90669991.937389.815510001.95390.539110011.97 396.845
10032.01403.088910062.06418.402410082.09431.110110092.11433.322410102.12431.1364
10132.12430.244410152.12431.2789 10202.3428.643810212.39430.149210232.69455.4127
10242.98470.781610263.57497.658910273.59508.419610284.46513.908410300.95515.4521
#Mann= 3 , 0 , 0
9699.037  0.0831       09699.037  0.0831       010300.95  0.0831       0
#XS Ineff= 2 , 0
       0                               0
Bank Sta=9699.037,10300.95
Exp/Cntr=0.3,0.1

Type RM Length L Ch R = 1 ,17710.74,141.689200,141.689200,141.689200
XS GIS Cut Line= 6
718444.159740105 825847.77647856 718635.96796433825820.194646148
718801.298236905825840.860477536718869.039481545825839.995450133
718944.326148741825821.806763346719027.276396019825775.716787482
#Sta/Elev= 30
9699.062471.16199711.852466.88159730.656464.11489811.928460.81469872.195454.3597
 9882.21450.49959902.227433.67899912.227426.20059922.228419.01749932.234413.4263
9942.268409.67949972.517395.97499982.699389.58379992.881387.1396 10003.1386.9256
10033.78399.853210043.87404.964510053.96411.137610084.03425.607910094.04429.3981
10104.05430.163210114.08428.7271 10134.2427.5267 10206.5425.606310217.51430.6862
10239.55454.614310265.01476.8963 10286.3491.529810298.16495.693110300.86497.5203
#Mann= 3 , 0 , 0
9699.062  0.0457       09699.062  0.0457       010300.86  0.0457       0
#XS Ineff= 2 , 0
       0                               0
Bank Sta=9699.062,10300.86
Exp/Cntr=0.3,0.1

Type RM Length L Ch R = 1 ,17569.06,141.689200,141.689200,141.689200
XS GIS Cut Line= 6
718483.059456324826100.033180277718652.361059843826009.761495232
718815.085257235825944.708661652718882.514873099825912.760499196
718954.838584156825867.456248581719011.974282502825819.433585254
#Sta/Elev= 30
9699.032455.21859712.739453.59049747.178453.50579758.657452.0051 9860.38451.3752
9871.555450.66919915.648423.48739937.461414.26349948.368 408.3979959.274398.9616
9969.979394.3632 9980.66387.43689991.341384.1238    9999384.114510002.01384.1223
10023.39393.409310044.78400.663310066.17 413.19310088.29424.008910099.36428.3444
10143.74426.499410226.48424.916110230.19425.922910239.31 431.86310246.14441.1304
10252.15447.863110264.99458.468310278.04468.717910291.53478.137610300.94483.4185
#Mann= 3 , 0 , 0
9699.032    0.04       09699.032    0.04       010300.94    0.04       0
#XS Ineff= 2 , 0
       0                               0
Bank Sta=9699.032,10300.94
Exp/Cntr=0.3,0.1

Type RM Length L Ch R = 1 ,17427.37,188.903300,188.903300,188.903300
XS GIS Cut Line= 3
718903.434599251826237.861635923718846.625077903826088.223206624
718833.990154803825966.160247028
#Sta/Elev= 30
 9821.79436.73859824.851436.62179835.547433.14289846.244 426.483 9856.94421.3393
9867.636409.40089873.729404.23679878.333401.99299889.029399.45529899.726396.3116
9901.904396.48229910.422398.55349921.118 398.0639931.815397.16999942.511393.9335
9953.208390.16489963.904386.2805  9974.6384.2415 9985.09383.69159995.143 383.459
 10005.2384.388910015.25389.2339 10025.3391.556810035.36393.165610045.41395.3006
10065.52402.722310075.57406.636810085.62410.200810095.68414.489410104.56417.9897
#Mann= 3 , 0 , 0
 9821.79  0.0644       0 9821.79  0.0644       010104.56  0.0644       0
#XS Ineff= 2 , 0
       0                               0
Bank Sta=9821.79,10104.56
Exp/Cntr=0.3,0.1

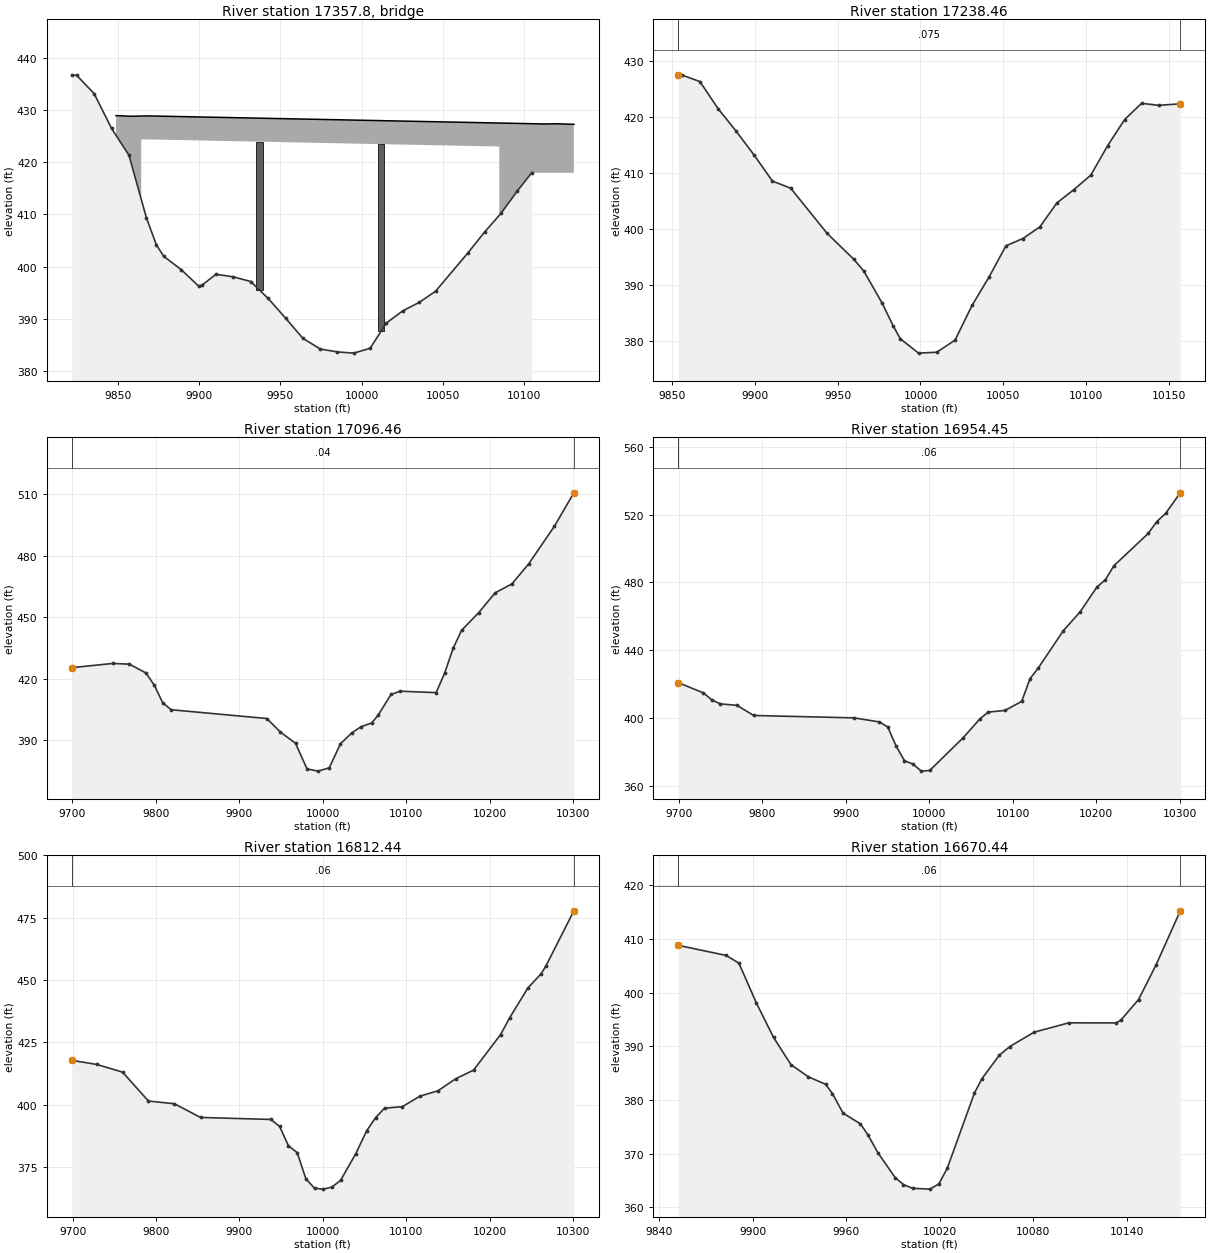
Type RM Length L Ch R = 3 , 17357.8,,,
BEGIN DESCRIPTION:
END DESCRIPTION:
Bridge Culvert--1,0,-1,-1, 0
Deck Dist Width WeirC Skew NumUp NumDn MinLoCord MaxHiCord MaxSubmerge Is_Ogee
48.355950,92.191400,2.6,0, 12, 12, , , 0.95, 0, 0,0,,
 9849.03 9858.15 9858.59 9864.48 9864.48 9867.5510084.6210084.6210112.6610119.68
10129.8010130.44
  428.93  428.81  428.81  428.85  428.85  428.88  427.51  427.51  427.33  427.37
  427.27  427.27
 -571.07 -571.19 -571.19 -571.15  424.35  424.38  423.01 -572.49 -572.67 -572.63
 -572.73 -572.73
 9849.03 9858.15 9858.59 9867.55 9874.01 9874.0110094.1510094.1510112.6610119.68
10129.8010130.44
  428.93  428.81  428.81  428.88  428.84  428.84  427.45  427.45  427.33  427.37
  427.27  427.27
 -571.07 -571.19 -571.19 -571.12 -571.16  424.34  422.95 -572.55 -572.67 -572.63
 -572.73 -572.73
Pier Skew, UpSta & Num, DnSta & Num=  ,9937.19, 2 ,9946.73, 2 , 0 , 0 , 0 ,,
    4.00    4.00
 -571.56  428.44
    4.00    4.00
 -571.62  428.38
Pier Skew, UpSta & Num, DnSta & Num=  ,10011.91, 2 ,10021.44, 2 , 0 , 0 , 0 ,,
    4.00    4.00
 -572.03  427.97
    4.00    4.00
 -572.09  427.91
BR Coef=-1 , 0 , 0 ,, 0 ,,,0.8,0,1,0,
WSPro=,,,, 1 ,,,, 0 ,,,, 0 ,,,,-1 ,-1 ,-1 , 0 , 0 , 0 , 0 , 0
BC Design=,, 0 ,, 0 ,,,,,,

Type RM Length L Ch R = 1 ,17238.46,142.006000,142.006000,142.006000
XS GIS Cut Line= 4
719078.546529979826276.973273411719055.877870947 826225.60193263
719009.337377101826125.014413714718980.691543698825992.201913714
#Sta/Elev= 30
9853.877427.56499856.034427.53659866.964426.35659877.894421.51769888.825417.4727
9899.755413.16359910.691408.54969921.709407.27939943.746 399.1729959.747394.5685
9965.783392.46579976.802386.75219983.561382.6193 9987.82380.33319998.839 377.764
10009.86 377.92510020.87380.0993 10031.1386.297210041.33391.376510051.56396.9705
10061.79398.276210072.02400.352210082.25404.640610092.48  407.0110102.71409.5984
10112.94414.908710123.17419.5684 10133.4422.470610143.63422.104610156.73422.3719
#Mann= 3 , 0 , 0
9853.877   0.075       09853.877   0.075       010156.73   0.075       0
#XS Ineff= 2 , 0
       0                               0
Bank Sta=9853.877,10156.73
Exp/Cntr=0.3,0.1

Type RM Length L Ch R = 1 ,17096.46,142.006000,142.006000,142.006000
XS GIS Cut Line= 6
719208.169567768826383.698009097719214.035061253826278.470098993
719198.226570016826189.128913227 719074.67328915825980.228796288
719067.870234185825895.449985768719084.625516484825822.897947442
#Sta/Elev= 30
9699.166 425.3559748.124427.40889768.128427.0777 9788.13422.76269798.131416.7462
 9808.15408.21819818.204  404.839932.935400.53869949.224393.88669967.271 388.485
9981.046375.96219994.253374.874310007.71376.481110021.06388.1723 10034.4393.4175
10045.48396.479610058.84398.432410066.24402.175310081.82412.3171   10093413.8673
 10135.8 413.178 10146.1422.816910156.22434.858710166.34443.599510186.58452.0941
10206.59461.887910226.59466.233410246.76476.026810277.57494.387310300.82510.6642
#Mann= 3 , 0 , 0
9699.166    0.04       09699.166    0.04       010300.82    0.04       0
#XS Ineff= 2 , 0
       0                               0
Bank Sta=9699.166,10300.82
Exp/Cntr=0.3,0.1

Type RM Length L Ch R = 1 ,16954.45,142.005900,142.005900,142.005900
XS GIS Cut Line= 6
719271.807999396826335.050947003719281.114233891826202.092602991
719261.024056531826009.539035201719256.322551682825895.940639559
719264.903819343825811.685173961719285.468373413825738.258796657
#Sta/Elev= 30
9699.066420.81759729.311414.75369739.375410.6063 9749.44408.27919769.551407.3872
9789.558 401.4139909.869400.00539940.079397.62289950.149394.67479960.219  383.39
9970.288374.68939980.358372.77869990.428368.553210000.51368.935510040.69388.2884
10060.73399.429710070.75403.434910090.79404.3871 10110.8409.7493 10120.8423.1627
 10130.8429.525410160.84451.590310180.88462.615410201.06 477.34610211.16481.5815
10221.27489.817310262.39508.902610272.72515.905110283.27520.747810300.94532.9179
#Mann= 3 , 0 , 0
9699.066    0.06       09699.066    0.06       010300.94    0.06       0
#XS Ineff= 2 , 0
       0                               0
Bank Sta=9699.066,10300.94
Exp/Cntr=0.3,0.1

Type RM Length L Ch R = 1 ,16812.44,142.006000,142.006000,142.006000
XS GIS Cut Line= 6
719318.359296893826343.836770547719352.144016436826217.041479916
719395.568287285826085.725413366719417.731636381826008.262905759
719463.855316659825884.617818694719510.068221766825774.024620713
#Sta/Elev= 30
9699.029 417.7499728.872416.12329759.919413.03379790.966401.43299822.012 400.363
9853.464394.85579937.724394.05819948.257391.2354 9958.79383.4848 9969.31380.7616
 9979.68370.2687 9990.05366.471110000.41366.122910010.83366.912410021.26369.6106
10039.49380.314410052.62389.522310063.29394.767310073.96398.578110095.31399.1815
10116.66403.4267   10138405.549410159.35410.385610180.69413.8282 10213.2428.1093
10224.04434.856610245.72446.686210261.88452.545310267.39 455.53410300.96477.7006
#Mann= 3 , 0 , 0
9699.029    0.06       09699.029    0.06       010300.96    0.06       0
#XS Ineff= 2 , 0
       0                               0
Bank Sta=9699.029,10300.96
Exp/Cntr=0.3,0.1

Type RM Length L Ch R = 1 ,16670.44,75.030400,75.030400,75.030400
XS GIS Cut Line= 3
719451.524877071826269.910247043719575.395053715826016.870634913
719593.909863055825981.244413182
#Sta/Elev= 30
9852.355408.82189883.003406.94329891.223  405.519902.357398.13349913.491391.6395
9924.625 386.5769935.759384.30839946.893382.90219951.235381.17089958.027377.5412
9969.161375.53389973.979373.48619980.295370.17919991.428365.51739996.723364.2163
10002.56363.5194 10013.7363.367710019.47364.345810024.83367.260510042.21381.2514
 10047.1383.977610058.23388.343410064.96389.9591 10080.5392.627710102.77394.3705
10133.19394.358710136.19394.893610147.46398.709110158.73 405.19910174.24415.2542
#Mann= 3 , 0 , 0
9852.355    0.06       09852.355    0.06       010174.24    0.06       0
#XS Ineff= 2 , 0
       0                               0
Bank Sta=9852.355,10174.24
Exp/Cntr=0.3,0.1