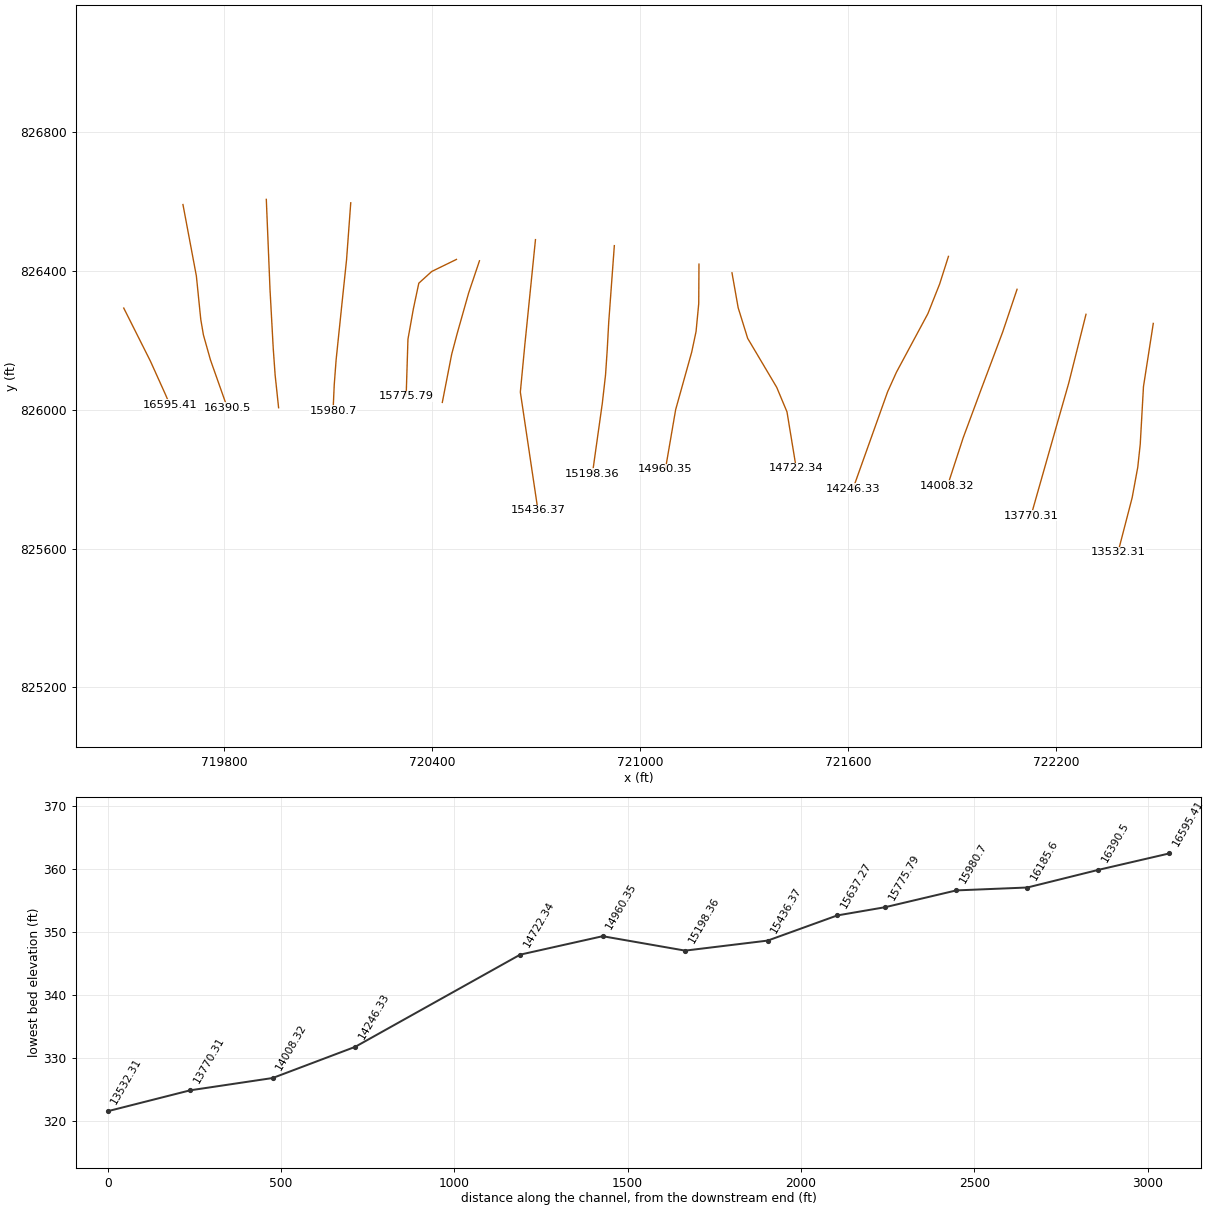
HEC-RAS study 14876_ras.prj: 14876

--- 14876_ras.g01 (geometry) --- (continued)

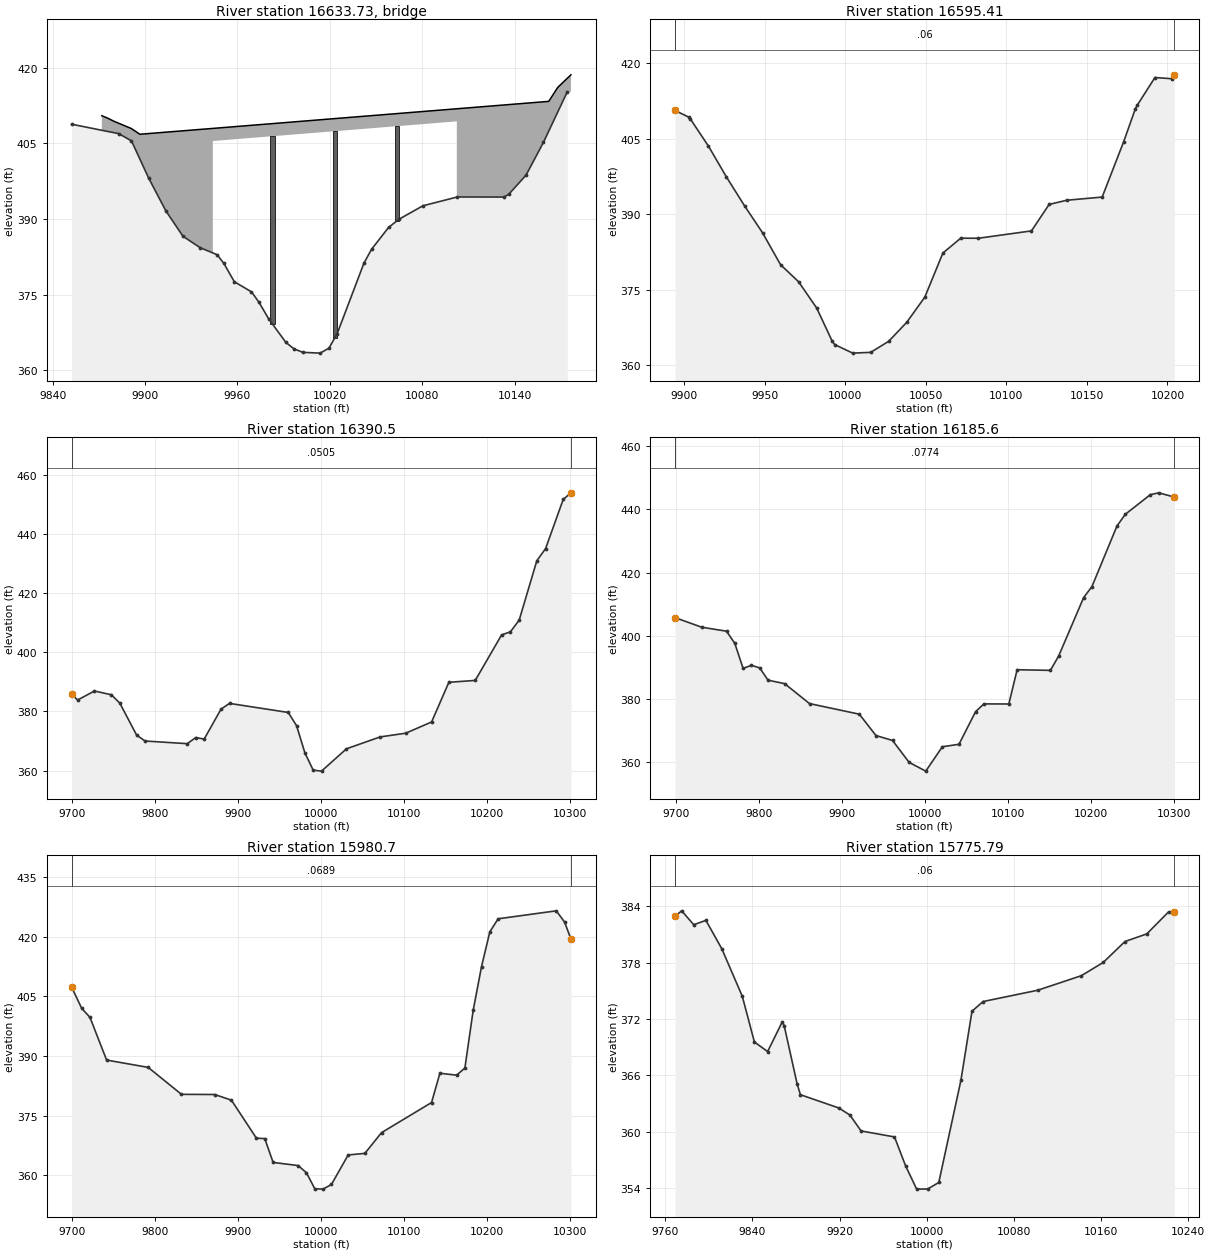
Type RM Length L Ch R = 3 ,16633.73,,,
BEGIN DESCRIPTION:
END DESCRIPTION:
Bridge Culvert--1,0,-1,-1, 0
Deck Dist Width WeirC Skew NumUp NumDn MinLoCord MaxHiCord MaxSubmerge Is_Ogee
16.189800,42.650800,2.6,0, 12, 12, , , 0.95, 0, 0,0,,
 9871.95 9875.50 9879.96 9891.04 9896.68 9944.05 9944.0510102.5110102.5110162.20
10168.0010176.61
  410.51  410.06  409.39  407.98  406.83  407.99  407.99  411.89  411.89  413.36
  416.12  418.63
 -589.49 -589.94 -590.61 -592.02 -593.17 -592.01  405.49  409.39 -588.11 -586.64
 -583.88 -581.37
 9871.95 9875.50 9879.96 9891.04 9896.68 9960.05 9960.0510118.5110118.5110162.20
10168.0010176.61
  410.51  410.06  409.39  407.98  406.83  408.39  408.39  412.28  412.28  413.36
  416.12  418.63
 -589.49 -589.94 -590.61 -592.02 -593.17 -591.61  405.89  409.78 -587.72 -586.64
 -583.88 -581.37
Pier Skew, UpSta & Num, DnSta & Num=  ,9982.91, 2 ,9998.91, 2 , 0 , 0 , 0 ,,
    3.00    3.00
 -591.05  408.95
    3.00    3.00
 -590.66  409.34
Pier Skew, UpSta & Num, DnSta & Num=  ,10023.28, 2 ,10039.28, 2 , 0 , 0 , 0 ,,
    3.00    3.00
 -590.06  409.94
    3.00    3.00
 -589.67  410.33
Pier Skew, UpSta & Num, DnSta & Num=  ,10063.65, 2 ,10079.64, 2 , 0 , 0 , 0 ,,
    3.00    3.00
 -589.07  410.93
    3.00    3.00
 -588.67  411.33
BR Coef=-1 , 0 , 0 ,, 0 ,,,0.8,0,1,0,
WSPro=,,,, 1 ,,,, 0 ,,,, 0 ,,,,-1 ,-1 ,-1 , 0 , 0 , 0 , 0 , 0
BC Design=,, 0 ,, 0 ,,,,,,

Type RM Length L Ch R = 1 ,16595.41,204.903900,204.903900,204.903900
XS GIS Cut Line= 4
719511.247099251826293.521358132719588.330432653826140.049135923
719632.168674171826042.842600256719644.577357084826013.928869024
#Sta/Elev= 30
9894.441410.59939902.802409.30059903.976408.89819915.167 403.5219926.357397.3795
9937.548391.67379948.738386.31159959.929379.96469971.119376.5794 9982.31371.3785
9991.923364.8053  9993.5364.110910004.69362.411810015.88362.567110027.07364.7751
10038.26 368.55210049.45373.543110060.64382.289210071.72385.238810082.69385.2287
 10115.6386.686110126.57391.944510137.54392.777710159.48393.402810172.82404.3877
   10180410.876510181.35 411.69910192.23417.149210203.12416.892310204.28417.6814
#Mann= 3 , 0 , 0
9894.441    0.06       09894.441    0.06       010204.28    0.06       0
#XS Ineff= 2 , 0
       0                               0
Bank Sta=9894.441,10204.28
Exp/Cntr=0.3,0.1

Type RM Length L Ch R = 1 , 16390.5,204.903800,204.903800,204.903800
XS GIS Cut Line= 6
719681.948554831 826592.04375592719720.601574066 826386.22550442
719733.306710069826260.874653751 719740.94307311826216.056447777
719761.242208667 826143.96745431719809.919349712826006.217780466
#Sta/Elev= 30
9699.024385.92659706.191383.88149726.541386.9354 9746.89385.66999757.065 382.845
9777.415371.9838 9787.59369.99769838.464369.09929848.639371.17229858.813370.6593
9879.163380.81449889.338382.73689960.113379.67879970.174375.2024  9980.2366.0029
9990.227360.123110000.25359.798610030.35367.363510070.88371.382610101.82 372.647
10132.99376.456410153.77389.891410185.56390.517410217.38405.953210227.99 406.989
10238.59410.982910259.81431.060410270.41435.197710291.62451.826910300.94454.0679
#Mann= 3 , 0 , 0
9699.024  0.0505       09699.024  0.0505       010300.94  0.0505       0
#XS Ineff= 2 , 0
       09927.407                       0
Bank Sta=9699.024,10300.94
Exp/Cntr=0.3,0.1

Type RM Length L Ch R = 1 , 16185.6,204.903900,204.903900,204.903900
XS GIS Cut Line= 6
719922.272614831826606.980562618719932.914413815826347.692607993
719935.252542928826305.270019892719942.186613723826178.270507889
719947.671365884826100.816545341719957.698481826826006.191819256
#Sta/Elev= 30
9699.007 405.6979731.014402.65929761.039  401.399771.048397.52079781.056 389.592
9791.065390.55299801.073389.75589811.082385.84759831.098384.75449861.124378.4228
9921.174 375.0639941.191368.2956 9961.21366.7326 9981.24359.766410001.27356.9981
 10021.3364.731610041.33365.511510061.36375.878910071.37378.324610101.42378.2963
10111.43389.163110151.52388.962210161.54393.540110191.62412.058710201.64415.5523
 10231.8434.764310241.85438.476310272.02 444.69410282.08 445.28310300.99443.9389
#Mann= 3 , 0 , 0
9699.007  0.0774       09699.007  0.0774       010300.99  0.0774       0
#XS Ineff= 2 , 0
       0                               0
Bank Sta=9699.007,10300.99
Exp/Cntr=0.3,0.1

Type RM Length L Ch R = 1 , 15980.7,204.903800,204.903800,204.903800
XS GIS Cut Line= 6
720165.726883541 826597.04679337720153.642340055 826432.89630867
 720139.32414098826296.252779342720123.448177507826143.178091093
720118.120478204826071.954263672720114.715004484825997.358782307
#Sta/Elev= 30
9699.014407.33069711.093402.0039 9721.12399.71579741.174388.9822 9791.31387.1391
9831.418380.36329871.548380.32279891.657378.89659921.821 369.3399931.876369.2383
9941.931 363.2469972.095362.46549982.149360.64649992.204356.616910002.26356.5381
10012.31357.735710032.42365.127310052.53365.523610072.63370.733910132.96378.3106
10143.01385.6659 10163.1385.188310173.12386.967610183.15401.499410193.18412.4686
10203.21  421.2210213.24424.493210283.33 426.49510293.34423.662210300.99419.4011
#Mann= 3 , 0 , 0
9699.014  0.0689       09699.014  0.0689       010300.99  0.0689       0
#XS Ineff= 2 , 0
       0                               0
Bank Sta=9699.014,10300.99
Exp/Cntr=0.3,0.1

Type RM Length L Ch R = 1 ,15775.79,138.526900,138.526900,138.526900
XS GIS Cut Line= 6
720470.448488176826433.799135908720399.267932624826399.076913714
720361.941543728826365.222747043720346.316543728826291.438024819
720330.691543728826203.764413685720325.483210385826039.701913685
#Sta/Elev= 30
9769.026382.91759775.088383.50119786.214382.02059797.341382.48469811.905379.4666
 9830.72374.40869841.846 369.5359853.986 368.5229867.486371.69899869.177371.2737
9880.986 365.1119884.062363.92689919.287362.51619929.509361.76189939.731360.0682
9970.396359.43219980.576356.36219990.734353.875710000.89353.888710011.05 354.582
10031.36365.454110041.52372.813610051.68373.844110101.88375.0488 10141.9376.5975
10161.91378.001410181.92380.235310201.93381.044510221.94383.391910227.24383.3738
#Mann= 3 , 0 , 0
9769.026    0.06       09769.026    0.06       010227.24    0.06       0
#XS Ineff= 2 , 0
       0                               0
Bank Sta=9769.026,10227.24
Exp/Cntr=0.3,0.1

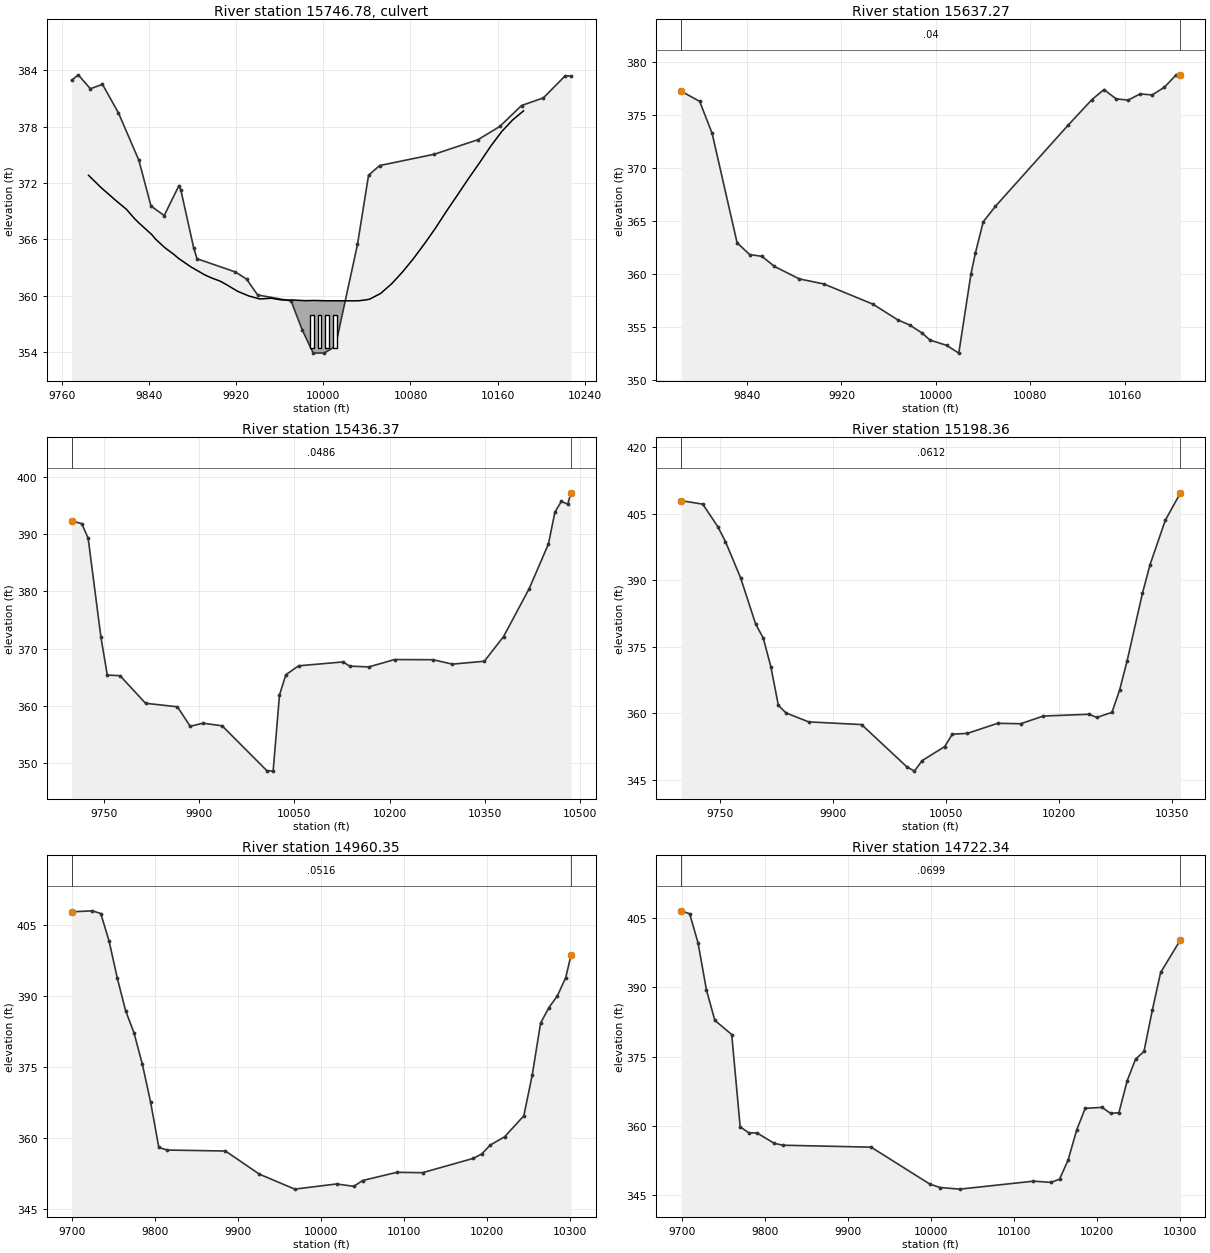
Type RM Length L Ch R = 2 ,15746.78,,,
Bridge Culvert--1,0,-1,-1, 0
Deck Dist Width WeirC Skew NumUp NumDn MinLoCord MaxHiCord MaxSubmerge Is_Ogee
58.013,22.5,2.6,0,54,54, , , 0.95, 0, 0,0,,
 9784.50 9784.66 9786.32 9796.20 9806.39 9807.73 9819.27 9826.45 9830.80 9842.34
 9842.53 9845.98 9854.56 9863.33 9866.80 9879.04 9880.68 9891.27 9898.03 9903.51
 9905.66 9911.35 9921.50 9931.65 9941.80 9951.95 9953.77 9962.10 9972.25 9981.73
 9982.39 9992.3910002.4010012.4110022.4210032.4210038.2410042.4810052.5910058.60
10062.7010072.8110082.9310093.0410103.1510113.2710123.3810125.6010133.4910143.61
10153.7210163.8310173.9510183.78
  372.81  372.79  372.60  371.48  370.45  370.30  369.19  368.23  367.73  366.52
  366.50  366.02  365.10  364.34  363.99  363.01  362.91  362.20  361.85  361.62
  361.52  361.15  360.45  359.96  359.64  359.72  359.69  359.53  359.53  359.47
  359.46  359.48  359.45  359.45  359.44  359.45  359.53  359.62  360.23  360.84
  361.26  362.53  363.97  365.55  367.22  369.03  370.75  371.14  372.50  374.18
  375.92  377.48  378.72  379.67
                                                                                
                                                                                
                                                                                
                                                                                
                                                                                
                                
 9784.50 9784.66 9786.32 9796.20 9806.39 9807.73 9819.27 9826.45 9830.80 9842.34
 9842.53 9845.98 9854.56 9863.33 9866.80 9879.04 9880.68 9891.27 9898.03 9903.51
 9905.66 9911.35 9921.50 9931.65 9941.80 9951.95 9953.77 9962.10 9972.25 9981.73
 9982.39 9992.3910002.4010012.4110022.4210032.4210038.2410042.4810052.5910058.60
10062.7010072.8110082.9310093.0410103.1510113.2710123.3810125.6010133.4910143.61
10153.7210163.8310173.9510183.78
  372.81  372.79  372.60  371.48  370.45  370.30  369.19  368.23  367.73  366.52
  366.50  366.02  365.10  364.34  363.99  363.01  362.91  362.20  361.85  361.62
  361.52  361.15  360.45  359.96  359.64  359.72  359.69  359.53  359.53  359.47
  359.46  359.48  359.45  359.45  359.44  359.45  359.53  359.62  360.23  360.84
  361.26  362.53  363.97  365.55  367.22  369.03  370.75  371.14  372.50  374.18
  375.92  377.48  378.72  379.67
                                                                                
                                                                                
                                                                                
                                                                                
                                                                                
                                
BR Coef=-1 , 0 , 0 ,, 0 ,,,0.8,-1,,0,
WSPro=,,,, 1 ,,,, 0 ,,,, 0 ,,,,-1 ,-1 ,-1 , 0 , 0 , 0 , 0 , 0
Multiple Barrel Culv=2,3.5,3.5,22.5,0.013,0.4,1,58,1,354.404,354.246,4,Culvert #1, 0, 58.013
 9989.50 9989.50 9996.50 9996.5010003.5010003.5010010.5010010.50
Culvert Bottom n=0.013
BC Design=,, 0 ,, 0 ,,,,,,

Type RM Length L Ch R = 1 ,15637.27,200.899700,200.899700,200.899700
XS GIS Cut Line= 5
720536.876835704  826429.8855104720505.631450266826336.952148035
720472.575894743826220.007703587 720456.74256137826160.285481349
720429.705524355826021.477610961
#Sta/Elev= 30
9784.252 377.2099799.956376.24799810.506373.23189831.607362.95529842.157361.8421
9852.707361.66799863.257360.72339884.326359.5467 9905.11359.06969946.677357.1689
9967.461355.70839977.852355.20319988.244354.45359994.912353.7966   10009 353.297
10019.35352.5639 10029.7 360.04510033.39361.971710040.04364.921910050.39366.3801
10111.75373.990510132.12376.422310142.31 377.361 10152.5376.487510162.69 376.369
10172.87376.950710183.06376.857410193.25377.563510203.44378.746510207.03378.7475
#Mann= 3 , 0 , 0
9784.252    0.04       09784.252    0.04       010207.03    0.04       0
#XS Ineff= 2 , 0
       0                               0
Bank Sta=9784.252,10207.03
Exp/Cntr=0.3,0.1

Type RM Length L Ch R = 1 ,15436.37,238.007600,238.007600,238.007600
XS GIS Cut Line= 5
720698.339175642826490.918102816 720668.15531671826192.446585149
720667.917490274826190.460775807720654.720466971826051.368494377
720705.514239281825709.981985942
#Sta/Elev= 30
9699.006392.32989715.005391.86349725.056389.29559745.158372.00289755.209365.3693
9775.311365.26299815.515360.43569865.771359.81899885.873356.41229905.975356.9509
9936.128356.498810006.49348.667710016.53348.567810026.58361.887710036.62365.4318
10056.71366.988410127.02367.670710137.07366.931310167.38366.800510207.82368.0809
10268.48368.055210298.81367.284710349.36367.785510379.69372.106910420.13380.5033
10450.46388.313510460.57393.863810470.68395.745210480.79395.255510485.86397.2469
#Mann= 3 , 0 , 0
9699.006  0.0486       09699.006  0.0486       010485.86  0.0486       0
#XS Ineff= 2 , 0
       0                               0
Bank Sta=9699.006,10485.86
Exp/Cntr=0.3,0.1

Type RM Length L Ch R = 1 ,15198.36,238.007600,238.007600,238.007600
XS GIS Cut Line= 6
720925.725549251826473.550842673720909.580668569 826253.11831674
720905.155119747826172.266362473720900.345113784826100.638891697
720891.066100091826019.065331072720862.395769209825815.092611015
#Sta/Elev= 30
9699.004407.99719727.631407.21859747.685402.12029757.712398.77569777.765390.6167
9797.819380.14149807.846377.00189817.872370.57369827.899361.81229837.926360.1199
9868.006358.09019938.173357.48029998.263347.939910008.28346.976510018.31 349.336
10048.37352.5132 10058.4355.302110078.46 355.49810118.72357.772310148.92357.6673
10179.19359.403410239.78 359.81210249.88359.094910270.08360.231710280.17365.2287
10290.27371.926510310.47387.097910320.57393.558710340.76403.564710360.87409.7683
#Mann= 3 , 0 , 0
9699.004  0.0612       09699.004  0.0612       010360.87  0.0612       0
#XS Ineff= 2 , 0
       0                               0
Bank Sta=9699.004,10360.87
Exp/Cntr=0.3,0.1

Type RM Length L Ch R = 1 ,14960.35,238.007700,238.007700,238.007700
XS GIS Cut Line= 6
721169.754312348826420.106224707721169.070552138826306.343356983
721161.317298817826225.655047899721148.762579972 826166.46094658
721102.518309543826000.685458845721073.032101283825828.823468991
#Sta/Elev= 30
9699.055407.83539724.161408.04599734.162407.47349744.162401.68899754.162393.7847
9764.162386.92739774.162382.31839784.163 375.7629794.163367.73359804.163358.0766
9814.166357.5193 9884.49 357.315 9925.25352.43699968.015349.265510018.44350.3581
 10039.3349.855710049.74351.077610091.17352.816910122.11352.736810183.33355.7633
10193.53356.706210203.71358.575610221.02360.319810244.16364.748610254.27373.3221
10264.39384.3422 10274.5387.626110284.62390.080210294.73393.958310300.98398.6271
#Mann= 3 , 0 , 0
9699.055  0.0516       09699.055  0.0516       010300.98  0.0516       0
#XS Ineff= 2 , 0
       0                               0
Bank Sta=9699.055,10300.98
Exp/Cntr=0.3,0.1

Type RM Length L Ch R = 1 ,14722.34,476.015300,476.015300,476.015300
XS GIS Cut Line= 6
721264.929018876826395.157937281 721282.79365607826294.400694788
721310.203427739826206.133500014721393.923244091826064.951503203
721423.544823815825994.227180684721450.314374049825831.161524875
#Sta/Elev= 30
9699.068406.5029 9709.34405.86979719.452399.55559729.565389.40469739.677382.8255
9760.023379.76429770.221359.81459780.419358.53019790.618358.47469811.159356.2461
9821.511355.82949928.029355.41219998.814 347.42610011.11346.683810035.15346.3352
10123.77348.056210144.81347.796510155.16348.473710165.52352.627510175.87 359.131
10186.11 363.81110206.46364.005310216.64362.727610226.72362.8463 10236.8369.8135
10246.88374.448410256.95376.095710267.01 385.00810277.03393.170910300.93400.2243
#Mann= 3 , 0 , 0
9699.068  0.0699       09699.068  0.0699       010300.93  0.0699       0
#XS Ineff= 2 , 0
       0                               0
Bank Sta=9699.068,10300.93
Exp/Cntr=0.3,0.1

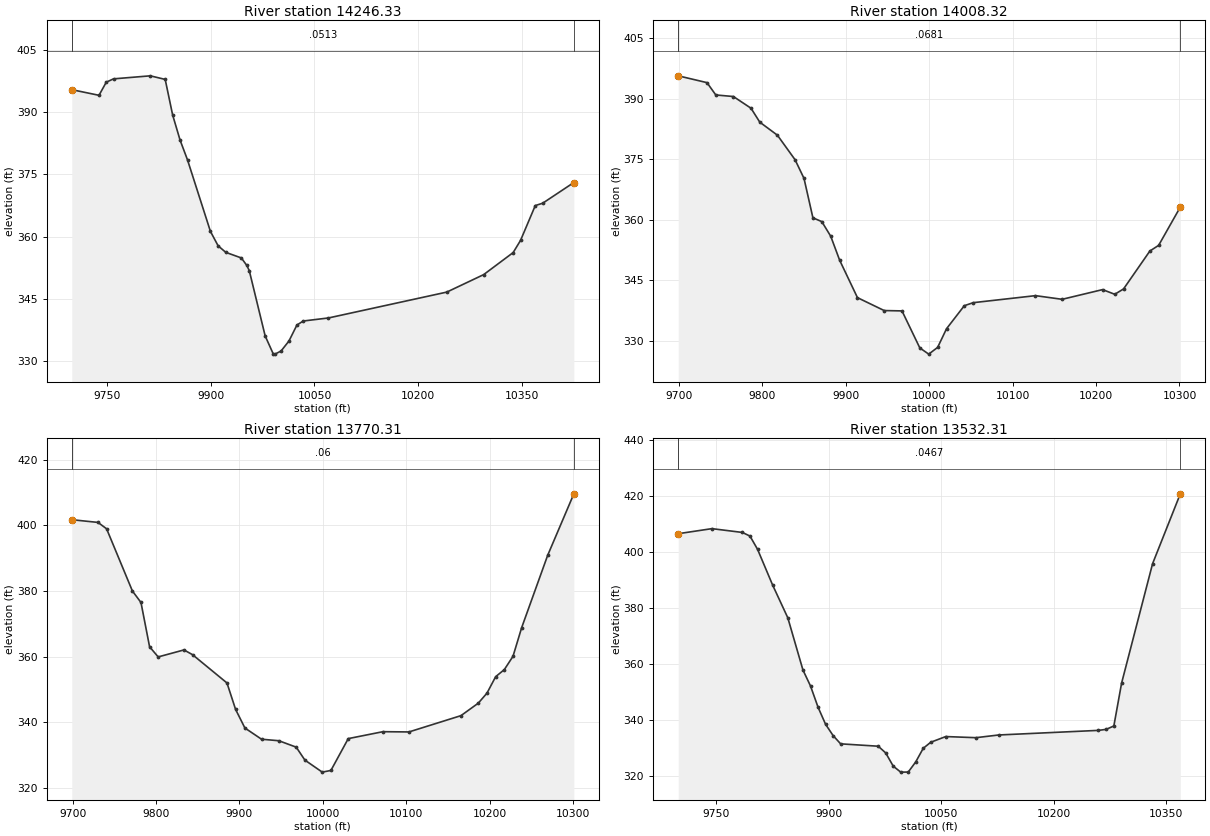
Type RM Length L Ch R = 1 ,14246.33,238.007600,238.007600,238.007600
XS GIS Cut Line= 6
721889.049395919 826442.51497592721863.762093842826363.137435704
721829.893972546826277.654051691721739.119594038826108.599351928
721713.652895242826052.189170778721613.858297586825772.734597936
#Sta/Elev= 30
9699.053395.35059738.426393.99169748.921397.15059759.416397.94949812.627  398.68
9834.139397.81589844.896389.25999855.652383.20729866.408378.43979899.542361.2351
 9910.68357.75899921.818356.18559944.226354.8477 9952.12353.0459 9955.71351.7943
9978.676336.07729990.159331.83129992.807331.696310001.65332.443810013.11334.8595
10024.56338.693610033.71339.666410070.21340.402710241.24346.625110294.57350.8305
10337.24356.139610347.91359.066610369.24367.454510379.91368.015410424.99373.0023
#Mann= 3 , 0 , 0
9699.053  0.0513       09699.053  0.0513       010424.99  0.0513       0
#XS Ineff= 2 , 0
       0                               0
Bank Sta=9699.053,10424.99
Exp/Cntr=0.3,0.1

Type RM Length L Ch R = 1 ,14008.32,238.007600,238.007600,238.007600
XS GIS Cut Line= 6
722086.884043389826347.671123518722045.188237222826223.801647544
721985.662369392826065.325034292721984.927043933826063.465115887
 721931.40428086825919.176051958721886.079919711825780.301701625
#Sta/Elev= 30
9699.014 395.7159733.486394.02619744.038 390.975 9765.14390.58679786.243387.6886
9796.794384.23559817.897381.00599839.115374.91489849.797370.30089860.479360.5329
9871.161359.58219881.843355.96569892.526 350.028 9913.89340.74769945.936337.5471
9967.301337.45959988.665328.2872 9999.35326.749410010.03328.420610020.69333.0458
10042.03 338.75210052.69339.500510127.35341.240510159.29340.333910207.77342.7381
 10222.4341.580710232.92342.905310264.48352.3005   10275353.704910300.98363.1958
#Mann= 3 , 0 , 0
9699.014  0.0681       09699.014  0.0681       010300.98  0.0681       0
#XS Ineff= 2 , 0
       0                               0
Bank Sta=9699.014,10300.98
Exp/Cntr=0.3,0.1

Type RM Length L Ch R = 1 ,13770.31,238.007700,238.007700,238.007700
XS GIS Cut Line= 5
722285.639906422826275.487734619722235.859998253826077.208663561
722209.659303785825985.312918639   722209.103192825983.391788846
722127.101160239825694.821460563
#Sta/Elev= 30
 9699.01401.67839730.444400.85069740.754398.91159771.685379.97369781.995376.4607
9792.306362.97699802.616359.88559833.547362.01559843.857360.56179885.099351.9527
9895.409 343.9179906.579338.23789926.536334.81889947.333334.3558 9968.13332.3989
9978.528  328.469999.326324.795710009.72325.308610030.52335.0034 10072.1337.1123
10103.29337.035410165.66342.000410186.45345.805310196.85348.858910207.25353.8655
10217.64356.021710228.04360.063510238.43368.795810269.62390.8256   10301409.5568
#Mann= 3 , 0 , 0
 9699.01    0.06       0 9699.01    0.06       0   10301    0.06       0
#XS Ineff= 2 , 0
       0                               0
Bank Sta=9699.01,10301
Exp/Cntr=0.3,0.1

Type RM Length L Ch R = 1 ,13532.31,238.007600,238.007600,238.007600
XS GIS Cut Line= 6
722479.655271471826249.283966795722451.354120791826067.138913468
722442.025866181 825900.81096454722434.885291129825834.618419826
722418.751009971825746.897486597722377.871348441825589.183207899
#Sta/Elev= 30
9699.025406.63489743.973408.43719784.573407.08139794.719405.78439804.811401.0616
9824.995388.25029845.179376.59159865.362357.95669875.454352.24169885.534344.6509
9895.569338.55559905.604334.52539915.639331.5768 9965.78330.73089975.785328.3267
9985.791323.61359995.796321.4749 10005.8321.501410015.81  325.1210025.82 329.984
10035.83332.147910055.87334.1778 10096.1333.776510126.38334.740410259.41336.3852
10269.74336.739710280.07337.9584 10290.4 353.26210331.72395.912610368.72420.8734
#Mann= 3 , 0 , 0
9699.025  0.0467       09699.025  0.0467       010368.72  0.0467       0
#XS Ineff= 2 , 0
       0                               0
Bank Sta=9699.025,10368.72
Exp/Cntr=0.3,0.1