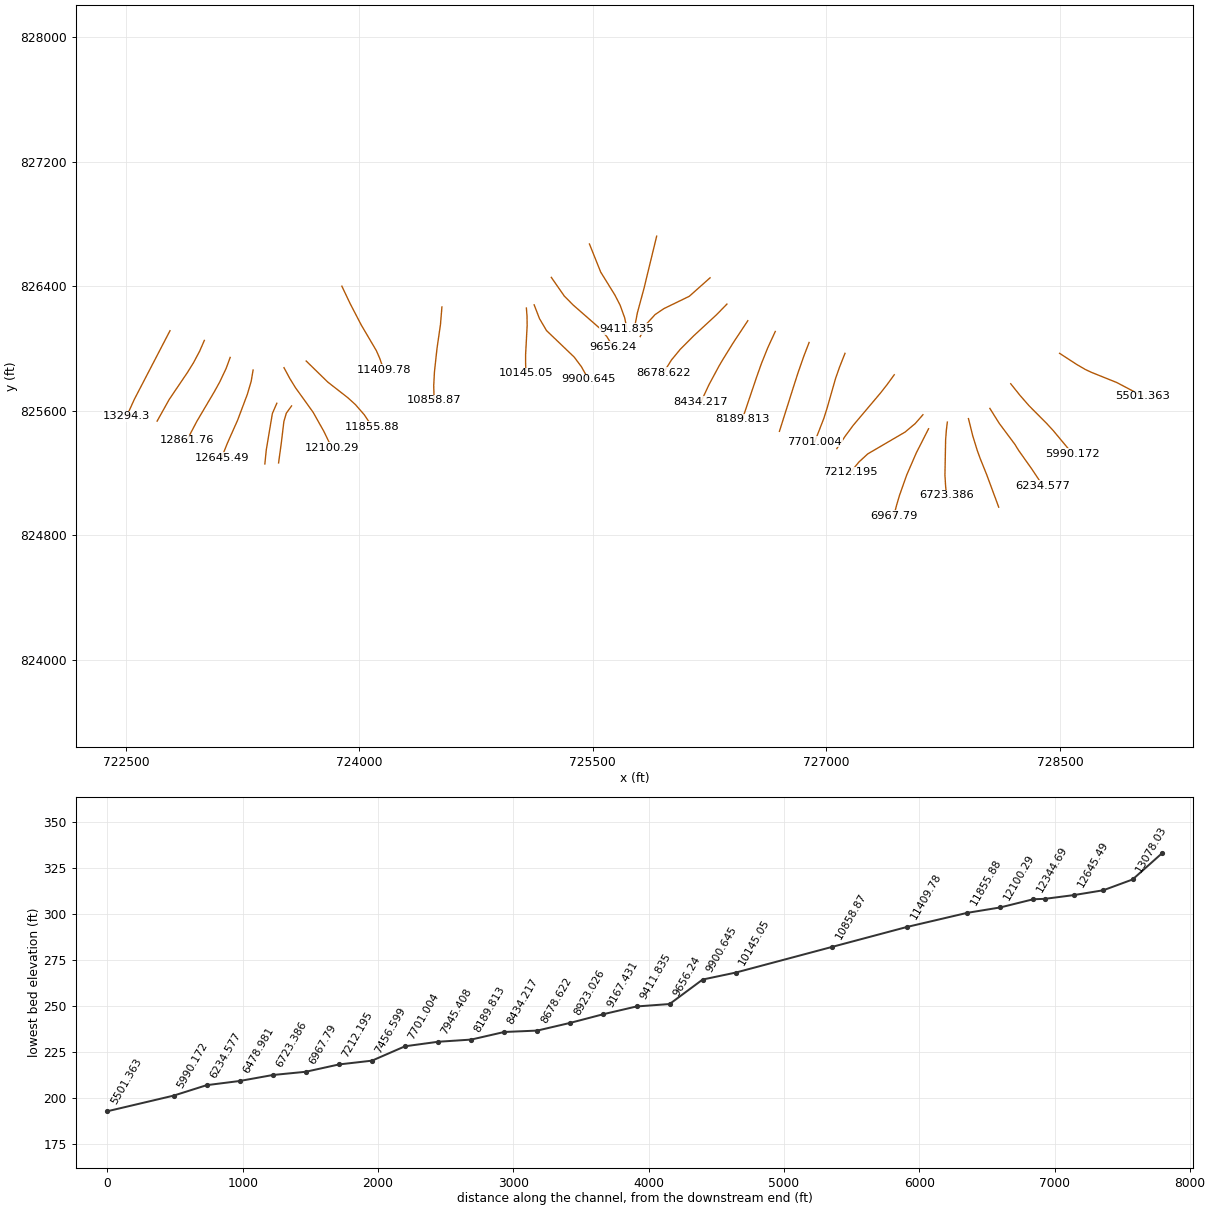
HEC-RAS study 14876_ras.prj: 14876

--- 14876_ras.g01 (geometry) --- (continued)

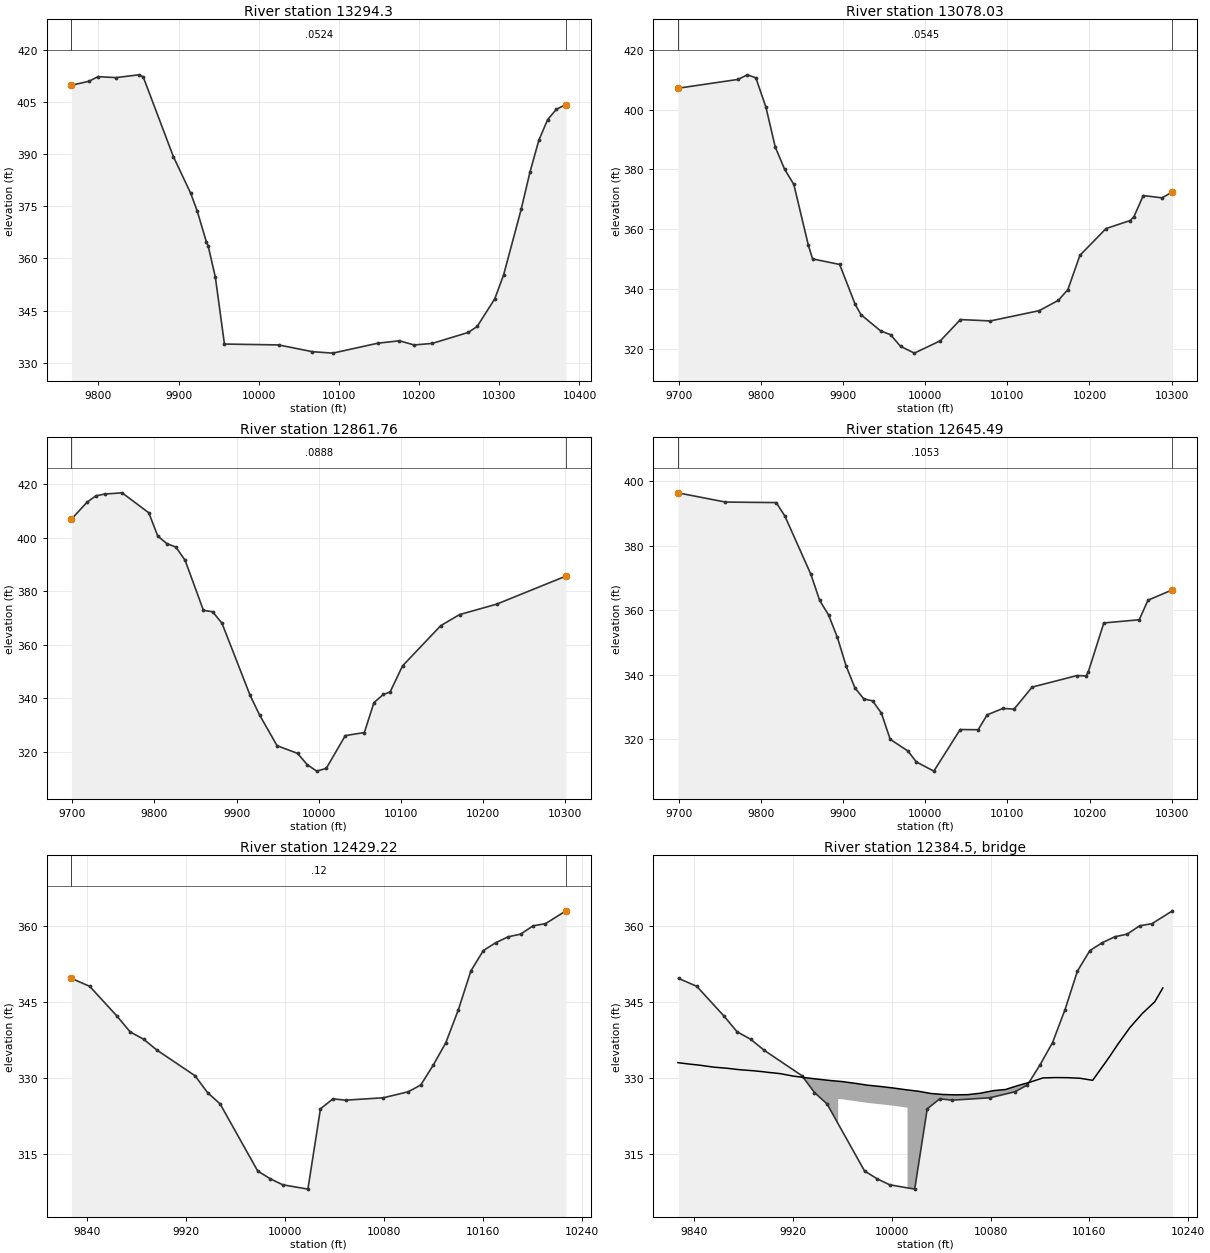
Type RM Length L Ch R = 1 , 13294.3,216.269400,216.269400,216.269400
XS GIS Cut Line= 3
722783.609315008826114.424157709 722554.60946247825673.424441651
722504.945387691 825564.08216311
#Sta/Elev= 30
9766.193 409.811 9788.08410.95569799.348412.28529821.883412.00349849.972412.8087
9855.687412.28189893.371389.3162 9915.07 378.7249923.294373.56419934.562364.7618
9936.769363.6625 9945.83354.56719957.098335.3942 10024.7335.142210066.96333.1914
10092.31332.782710148.65335.646710175.46 336.33310193.72335.131410216.26335.5758
10261.33338.735410272.36340.445110294.32348.384610305.31355.219410327.27374.1236
10338.26384.831710349.24393.927610360.22399.903110371.21402.9006 10383.2404.2746
#Mann= 3 , 0 , 0
9766.193  0.0524       09766.193  0.0524       0 10383.2  0.0524       0
#XS Ineff= 2 , 0
       0                               0
Bank Sta=9766.193,10383.2
Exp/Cntr=0.3,0.1

Type RM Length L Ch R = 1 ,13078.03,216.269400,216.269400,216.269400
XS GIS Cut Line= 6
723004.313544797 826052.15274631722974.496258038  825983.7049376
722934.446529699825908.284584773722895.028512454825844.913708135
722779.044692962825673.345736822722700.972463478825533.579356495
#Sta/Elev= 30
9699.049 407.1129772.297410.06569783.566411.59829793.957410.6034 9806.21400.7934
9817.533387.50519828.855380.10989840.178 374.9569857.924354.56939862.972350.0866
9895.922348.23919914.855334.90219921.856331.47239945.751326.03669957.872324.7648
9969.993320.88699986.868 318.60210018.56322.7468 10042.9329.818610079.26329.3601
10138.87332.798610162.12336.253710173.72 339.85310188.31 351.26910220.12360.2267
10249.49362.911310254.15 364.22810265.46371.257510288.07370.495110300.98372.4479
#Mann= 3 , 0 , 0
9699.049  0.0545       09699.049  0.0545       010300.98  0.0545       0
#XS Ineff= 2 , 0
       0                               0
Bank Sta=9699.049,10300.98
Exp/Cntr=0.3,0.1

Type RM Length L Ch R = 1 ,12861.76,216.269300,216.269300,216.269300
XS GIS Cut Line= 6
723170.373086155825942.946548319723144.623765782825872.872101254
723102.706012548825784.175552473723067.180141402825720.124963957
722956.130193475825532.031657977722892.280484284825410.274056745
#Sta/Elev= 30
9699.034406.88979718.154413.23179728.808415.59469739.462416.26489760.769416.7215
9793.214 409.2699804.138 400.567 9815.11397.76669826.268 396.4569837.425391.5077
 9859.74372.80319870.897 372.2979882.309367.99289916.615341.0007 9928.05 333.723
9949.325322.24549974.292319.37239985.927315.19589997.562312.742310009.18313.7639
10032.39 326.013 10055.6 327.16610067.21338.323310078.81341.443610086.88342.2765
10102.02352.056910148.44367.067310171.43371.2316 10216.6375.129510300.97385.6254
#Mann= 3 , 0 , 0
9699.034  0.0888       09699.034  0.0888       010300.97  0.0888       0
#XS Ineff= 2 , 0
       0                               0
Bank Sta=9699.034,10300.97
Exp/Cntr=0.3,0.1

Type RM Length L Ch R = 1 ,12645.49,216.269500,216.269500,216.269500
XS GIS Cut Line= 6
723317.674040024825862.103671214 723305.04378239825788.535896746
723280.877200092825706.662154935723218.021630126825539.388237101
723152.720939726825392.558801219723114.847021748825297.359858261
#Sta/Elev= 30
9699.053396.31769756.992393.45849818.783393.29249829.299389.11259860.887371.1044
9871.627362.98079882.367358.53529893.108 351.5919903.848342.67839914.588335.8739
9925.328332.50039936.068331.88979946.808328.0643 9957.45 319.9739978.782316.4113
9989.364312.963910010.57310.128510042.62323.013210064.51 322.94710075.46327.5643
10094.48329.528910108.29  329.3510130.18336.1585 10184.9339.731110195.85339.6044
10198.52340.848110217.42356.023610260.46357.001410271.23363.064710300.97366.2992
#Mann= 3 , 0 , 0
9699.053  0.1053       09699.053  0.1053       010300.97  0.1053       0
#XS Ineff= 2 , 0
       0                               0
Bank Sta=9699.053,10300.97
Exp/Cntr=0.3,0.1

Type RM Length L Ch R = 1 ,12429.22,84.530600,84.530600,84.530600
XS GIS Cut Line= 4
723470.043395579825648.556080356723441.397562265825582.583858132
723402.335062236  825349.0769137723393.003550202825258.509375811
#Sta/Elev= 30
  9827.5349.65789842.279348.08679864.083342.28149874.985339.09849885.887337.6469
9896.789335.4753 9927.39330.44959937.529 327.1219947.668324.89179978.085311.6426
9988.224310.11479998.363308.923110018.64308.068910028.78323.912110038.92325.8846
10049.06325.623310079.47326.091810099.75327.276510109.89328.631610120.03332.5823
10130.17 336.99310140.27343.484910150.33351.105510160.38355.138510170.43356.6919
10180.49 357.85910190.54358.383410200.59360.019910210.64360.453710227.22362.9843
#Mann= 3 , 0 , 0
  9827.5    0.12       0  9827.5    0.12       010227.22    0.12       0
#XS Ineff= 2 , 0
       0                               0
Bank Sta=9827.5,10227.22
Exp/Cntr=0.3,0.1

Type RM Length L Ch R = 3 , 12384.5,,,
BEGIN DESCRIPTION:
END DESCRIPTION:
Bridge Culvert--1,0,-1,-1, 0
Deck Dist Width WeirC Skew NumUp NumDn MinLoCord MaxHiCord MaxSubmerge Is_Ogee
27.993700,28.543200,2.6,0, 54, 54, , , 0.95, 0, 0,0,,
 9826.99 9834.62 9845.48 9849.02 9856.35 9867.21 9874.64 9878.07 9888.93 9896.38
 9899.57 9905.23 9909.72 9919.87 9930.02 9940.17 9950.32 9956.72 9956.72 9960.47
 9963.56 9970.62 9980.77 9990.9210001.0710011.2210012.8210012.8210014.6610021.34
10023.1110031.4510041.5610051.6710061.7810071.8910082.0010091.3510092.1110102.22
10112.3310117.0210122.4110132.4610142.5210152.5710162.6310172.6810176.9210182.73
10192.7910202.8410212.9010219.43
  333.03  332.79  332.50  332.37  332.13  331.91  331.69  331.61  331.41  331.22
  331.12  330.98  330.86  330.39  330.06  329.77  329.50  329.36  329.36  329.28
  329.17  328.94  328.57  328.32  328.03  327.69  327.64  327.64  327.59  327.39
  327.32  326.95  326.74  326.67  326.71  327.00  327.49  327.71  327.72  328.51
  329.20  329.58  330.01  330.08  330.06  329.94  329.54  332.95  334.43  336.55
  339.95  342.73  345.04  347.76
 -666.97 -667.21 -667.50 -667.63 -667.87 -668.09 -668.31 -668.39 -668.59 -668.78
 -668.88 -669.02 -669.14 -669.61 -669.94 -670.23 -670.50 -670.64  325.86  325.78
  325.67  325.44  325.07  324.82  324.53  324.19  324.14 -672.36 -672.41 -672.61
 -672.68 -673.05 -673.26 -673.33 -673.29 -673.00 -672.51 -672.29 -672.28 -671.49
 -670.80 -670.42 -669.99 -669.92 -669.94 -670.06 -670.46 -667.05 -665.57 -663.45
 -660.05 -657.27 -654.96 -652.24
 9826.99 9834.62 9845.48 9849.02 9856.35 9867.21 9874.64 9878.07 9888.93 9896.38
 9899.57 9905.23 9909.72 9919.87 9930.02 9940.17 9950.32 9960.47 9960.69 9960.69
 9963.56 9970.62 9980.77 9990.9210001.0710011.2210014.6610016.7910016.7910021.34
10023.1110031.4510041.5610051.6710061.7810071.8910082.0010091.3510092.1110102.22
10112.3310117.0210122.4110132.4610142.5210152.5710162.6310172.6810176.9210182.73
10192.7910202.8410212.9010219.43
  333.03  332.79  332.50  332.37  332.13  331.91  331.69  331.61  331.41  331.22
  331.12  330.98  330.86  330.39  330.06  329.77  329.50  329.28  329.27  329.27
  329.17  328.94  328.57  328.32  328.03  327.69  327.59  327.53  327.53  327.39
  327.32  326.95  326.74  326.67  326.71  327.00  327.49  327.71  327.72  328.51
  329.20  329.58  330.01  330.08  330.06  329.94  329.54  332.95  334.43  336.55
  339.95  342.73  345.04  347.76
 -666.97 -667.21 -667.50 -667.63 -667.87 -668.09 -668.31 -668.39 -668.59 -668.78
 -668.88 -669.02 -669.14 -669.61 -669.94 -670.23 -670.50 -670.72 -670.73  325.77
  325.67  325.44  325.07  324.82  324.53  324.19  324.09  324.03 -672.47 -672.61
 -672.68 -673.05 -673.26 -673.33 -673.29 -673.00 -672.51 -672.29 -672.28 -671.49
 -670.80 -670.42 -669.99 -669.92 -669.94 -670.06 -670.46 -667.05 -665.57 -663.45
 -660.05 -657.27 -654.96 -652.24
BR Coef=-1 , 0 , 0 ,, 0 ,,,0.8,0,1,0,
WSPro=,,,, 1 ,,,, 0 ,,,, 0 ,,,,-1 ,-1 ,-1 , 0 , 0 , 0 , 0 , 0
BC Design=,, 0 ,, 0 ,,,,,,

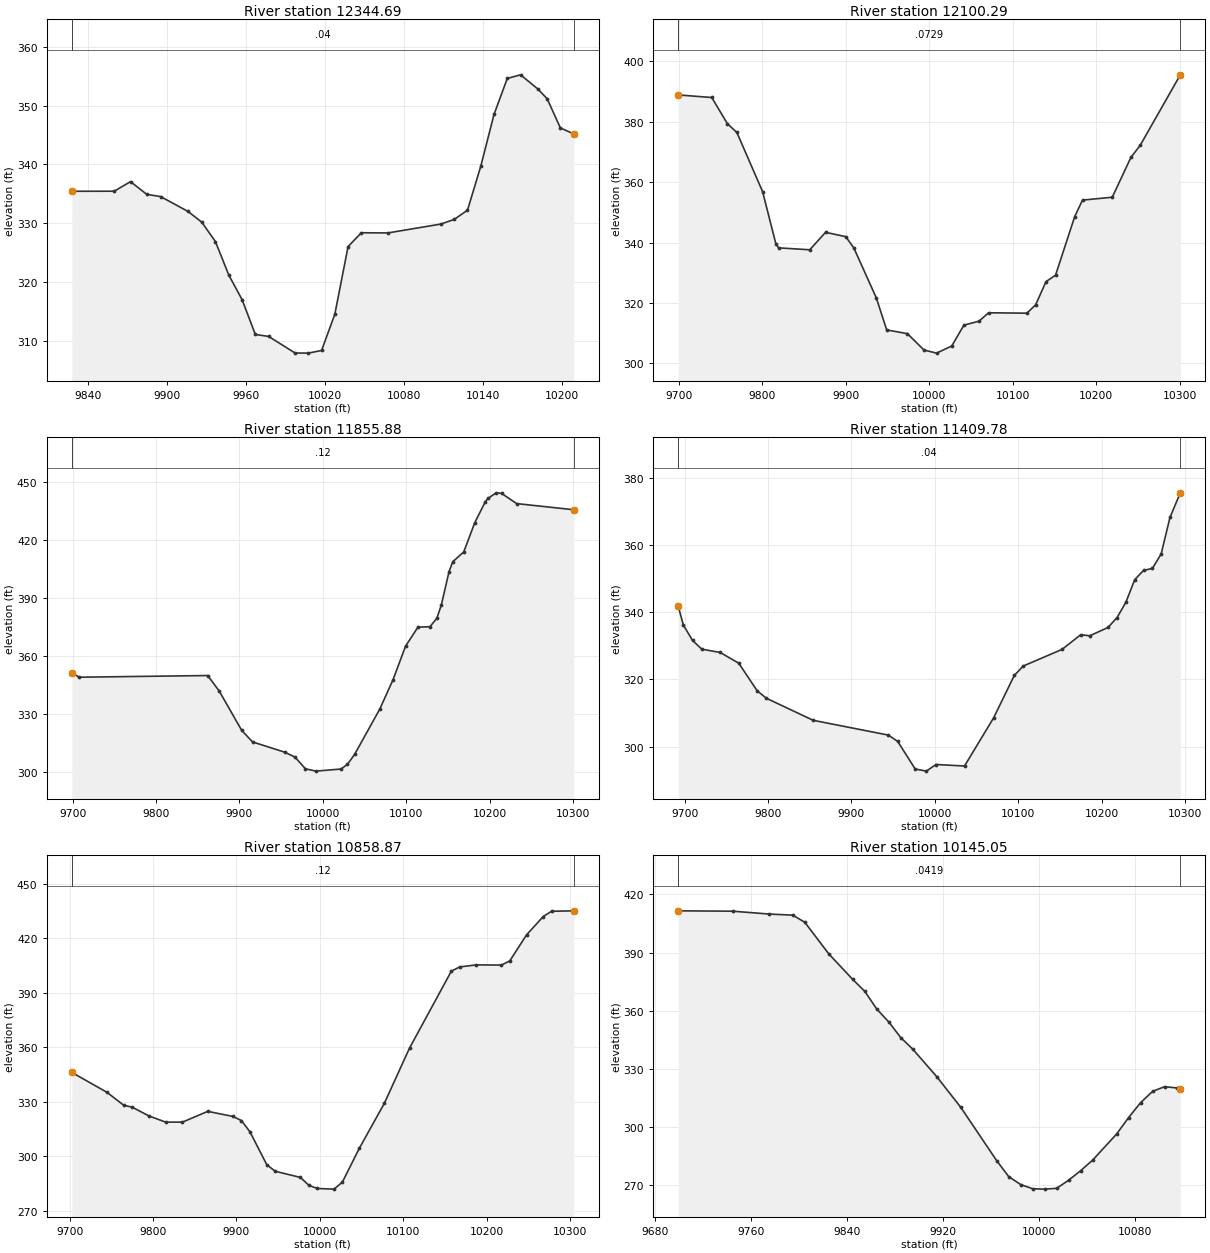
Type RM Length L Ch R = 1 ,12344.69,244.404400,244.404400,244.404400
XS GIS Cut Line= 5
723564.661451131825631.194969267723530.807284445825584.319969267
723515.182284445825530.500524804723500.425339997825406.368580356
723481.328117818825264.875524819
#Sta/Elev= 30
9827.415335.43569859.727335.44749872.063337.07889884.398334.91539894.942334.5308
9915.767332.0047 9926.18330.18599936.593326.87329946.818321.14239956.888316.9682
9966.959311.04219977.029310.7102 9997.17307.882710007.24307.863510017.31308.3156
10027.38314.491110037.45326.014110047.52328.369210067.67328.336510108.03329.8523
10118.12330.638310128.21332.2067 10138.3339.694410148.39 348.53310158.48354.6628
10168.57355.271910181.61352.874310188.75351.211210198.84346.221110209.06345.2073
#Mann= 3 , 0 , 0
9827.415    0.04       09827.415    0.04       010209.06    0.04       0
#XS Ineff= 2 , 0
       0                               0
Bank Sta=9827.415,10209.06
Exp/Cntr=0.3,0.1

Type RM Length L Ch R = 1 ,12100.29,244.404600,244.404600,244.404600
XS GIS Cut Line= 6
723515.967928518825876.916246316723553.433072816825807.225392427
723590.167440452 825747.63507965723702.872294079825590.794112252
723772.546887287825466.839879219723823.457190622825361.231437217
#Sta/Elev= 30
9699.045388.83629739.239387.98949757.987379.31349769.341376.4277 9800.21356.8221
9816.024339.65289819.267338.23659856.694337.60159875.649343.37769899.929341.9335
9909.607338.1842 9936.53  321.669948.955311.08669973.806309.84259993.665304.4256
10008.73303.401910026.97305.7722 10041.5312.659610059.62313.972210071.09316.7571
10116.98316.617610127.48 319.37710139.92327.046510151.39329.198910174.34348.5562
 10183.7354.040410219.38354.9853 10241.8 368.208 10252.8372.132310300.96395.4918
#Mann= 3 , 0 , 0
9699.045  0.0729       09699.045  0.0729       010300.96  0.0729       0
#XS Ineff= 2 , 0
       0                               0
Bank Sta=9699.045,10300.96
Exp/Cntr=0.3,0.1

Type RM Length L Ch R = 1 ,11855.88,446.096700,446.096700,446.096700
XS GIS Cut Line= 6
723658.690347888825919.655735158723798.207602439825783.642953625
723924.444797345825685.255841468723974.183701519825640.411660783
724031.219143497 825574.99646546724082.747639586825497.449447228
#Sta/Elev= 30
9699.024351.28649707.981348.9807 9861.97349.84599875.726341.87859902.732321.5207
9915.744315.5488 9954.16310.26279966.639307.71719979.118301.67499991.598300.4574
10021.69301.539810029.41303.894610038.05309.074910068.19332.431910084.23347.7392
10099.16 364.996 10114.1374.875110128.38375.046410136.73379.444610142.11386.3437
10151.32403.569410155.85408.676510168.94413.699110182.25428.898110194.83439.6698
   10198 441.33910207.78444.245310214.28443.959610232.39438.679310300.94435.5046
#Mann= 3 , 0 , 0
9699.024    0.12       09699.024    0.12       010300.94    0.12       0
#XS Ineff= 2 , 0
       0                               0
Bank Sta=9699.024,10300.94
Exp/Cntr=0.3,0.1

Type RM Length L Ch R = 1 ,11409.78,550.917500,550.917500,550.917500
XS GIS Cut Line= 6
723887.822956335826400.529389683723940.291186435826290.054717748
724011.972003009826151.815540754 724109.89688872825985.342659384
724132.222167359825933.976226926724156.192147572825863.259143861
#Sta/Elev= 30
9692.313341.74949698.435336.17069709.505 331.5869720.576329.00029742.717328.0155
9764.858324.83179786.999316.61749798.069314.40699854.102307.86559944.217 303.475
9955.481301.57779976.373293.40099989.766292.769110001.29294.736710035.53294.2921
 10070.4308.593210095.22321.208910105.96 323.99610152.43328.932310174.82333.2909
10185.72332.985710207.53335.453610218.44338.403410229.03 342.96210239.59 349.662
10250.15352.407610260.71352.979210271.27357.283710281.82368.143110294.22375.4485
#Mann= 3 , 0 , 0
9692.313    0.04       09692.313    0.04       010294.22    0.04       0
#XS Ineff= 2 , 0
       0                               0
Bank Sta=9692.313,10294.22
Exp/Cntr=0.3,0.1

Type RM Length L Ch R = 1 ,10858.87,713.817400,713.817400,713.817400
XS GIS Cut Line= 6
724530.429196407826267.159395562724521.040399842826153.366125527
724498.708146896825999.638454561 724482.43324908825849.252960966
724477.806679054825762.828313442724480.343348335825668.275616333
#Sta/Elev= 30
9702.573346.24479744.876335.25149764.944328.12459774.978327.12269795.046322.2551
9815.114318.87989835.312318.86599865.627324.79129895.942321.97529906.047319.6915
9916.152313.56199936.362 295.4419946.467291.81459976.765288.40589986.834284.0671
9996.903282.331310017.02281.974810027.08 285.90410047.19304.355510077.36329.2647
10107.53359.647510157.66402.003410167.68 404.311 10187.7405.449110217.74405.3273
10227.74407.667110247.75421.929710267.76432.042810277.76434.9549 10304.5435.2001
#Mann= 3 , 0 , 0
9702.573    0.12       09702.573    0.12       0 10304.5    0.12       0
#XS Ineff= 2 , 0
       09887.276                       0
Bank Sta=9702.573,10304.5
Exp/Cntr=0.3,0.1

Type RM Length L Ch R = 1 ,10145.05,244.404500,244.404500,244.404500
XS GIS Cut Line= 6
725072.975721559826260.462872336725077.044766795826208.484171198
725077.884805941826146.863500663725067.978592808825960.936908231
725068.154193462825896.654129082725070.807203486825841.879568538
#Sta/Elev= 30
9699.033411.49989744.635411.30849774.658409.84349794.659409.2728 9804.66405.6065
9824.681389.30929844.716376.09679854.733369.9981 9864.75360.84499874.767354.1952
9884.785346.12219894.802340.14789914.836325.9667 9934.87310.16439964.922282.5843
9974.927274.40239984.931 270.3199994.935268.167510004.94267.977310014.94268.4089
10024.94272.595310034.94277.485710044.94282.941510064.94296.394910074.95304.8857
10084.96312.569610094.97318.381410104.99320.8049   10115320.181710118.12319.4404
#Mann= 3 , 0 , 0
9699.033  0.0419       09699.033  0.0419       010118.12  0.0419       0
#XS Ineff= 2 , 0
       0                               0
Bank Sta=9699.033,10118.12
Exp/Cntr=0.3,0.1

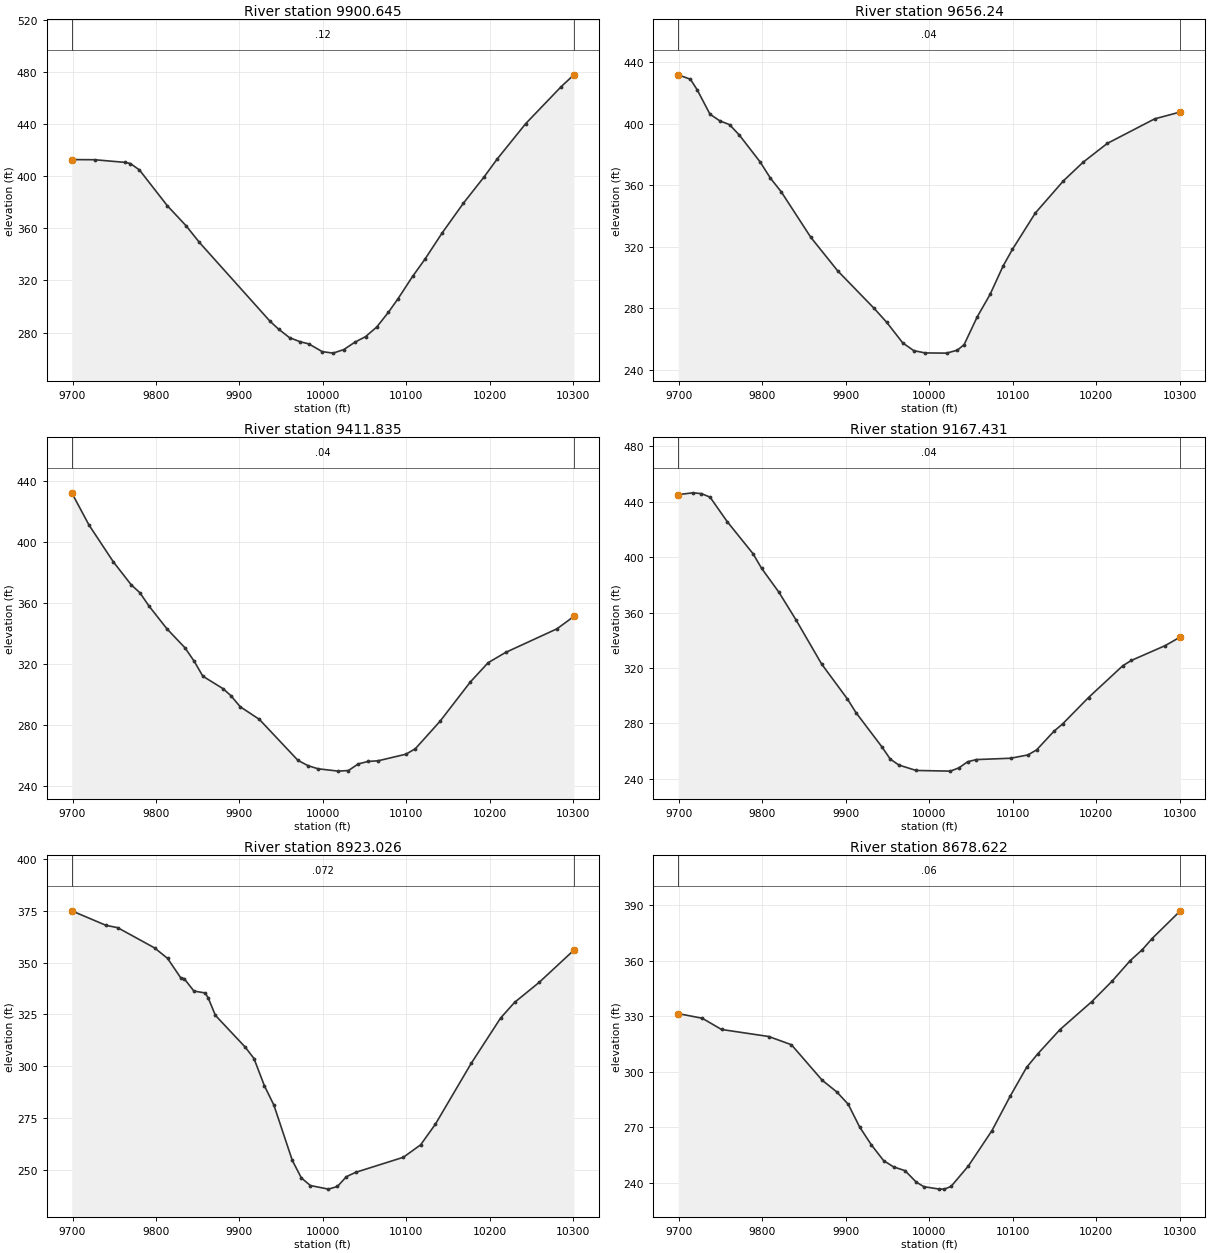
Type RM Length L Ch R = 1 ,9900.645,244.404500,244.404500,244.404500
XS GIS Cut Line= 6
 725122.92780104826280.836315336725157.219458645 826192.12981913
725202.374344699826115.357450023725380.917137782825944.285757374
725427.215147261825882.007111301725471.926272336825801.710472057
#Sta/Elev= 30
9699.093412.72759726.508412.61179763.054410.57229769.384409.69019780.253404.7434
9813.637377.31539836.282361.82139852.171349.09199936.959288.51819947.045 282.602
9960.101276.06999973.157272.8727 9983.27271.28619999.262265.360210012.23264.1909
10025.23266.920510038.24272.496410051.25276.846710064.67284.226810078.64295.5315
10089.86305.628610107.59323.013210122.52336.348510143.17356.505710168.63379.3177
10193.17399.264110208.98 413.10110243.28440.343510285.79468.709510300.95477.7688
#Mann= 3 , 0 , 0
9699.093    0.12       09699.093    0.12       010300.95    0.12       0
#XS Ineff= 2 , 0
       0                               0
Bank Sta=9699.093,10300.95
Exp/Cntr=0.3,0.1

Type RM Length L Ch R = 1 , 9656.24,244.404600,244.404600,244.404600
XS GIS Cut Line= 6
725233.096806542826457.448474524725316.322351188826337.510379341
725373.906260265 826279.26868478725545.163909042826129.424947155
725591.161459915826074.853380261725629.770263267826011.025236565
#Sta/Elev= 30
9699.059431.96489713.672429.09259721.787422.20889737.149406.33639748.888402.0334
9760.627399.52939772.365392.72259797.182375.33439809.641 364.6769822.517355.8657
9858.038326.19099890.096304.49669933.788  280.06 9949.12 270.8369968.262257.4889
9981.454 252.4889995.118251.000610020.76250.868810033.79252.811210041.84256.4782
10057.43274.4181 10072.9289.085110088.56307.640310099.59318.314910127.12342.0238
10160.86362.996210184.35375.065810213.35387.312310270.12403.297710300.95407.7917
#Mann= 3 , 0 , 0
9699.059    0.04       09699.059    0.04       010300.95    0.04       0
#XS Ineff= 2 , 0
       0                               0
Bank Sta=9699.059,10300.95
Exp/Cntr=0.3,0.1

Type RM Length L Ch R = 1 ,9411.835,244.404500,244.404500,244.404500
XS GIS Cut Line= 6
725478.047567202826671.925692044725550.659449884826490.959230271
725641.045641127826344.759178513725675.218364557826278.438425769
725704.217295353826198.181264387725719.496375579826125.126127507
#Sta/Elev= 30
9699.079 432.1559719.668411.09239748.933386.86689770.181371.90349780.805366.5709
9791.429358.04359812.979343.04569834.925330.38369845.898321.58879856.189311.8378
9880.478303.63739889.791299.07479901.034291.78079923.887283.53859970.126256.6692
9982.154253.16039994.183 251.09510018.52  249.55 10030.7 249.94910042.48 254.262
10054.23255.913910066.26256.331810099.74260.676210110.99264.279810140.39282.1804
 10176.9308.082410198.15320.680210219.12327.428710280.77342.953210300.93 351.051
#Mann= 3 , 0 , 0
9699.079    0.04       09699.079    0.04       010300.93    0.04       0
#XS Ineff= 2 , 0
       0                               0
Bank Sta=9699.079,10300.93
Exp/Cntr=0.3,0.1

Type RM Length L Ch R = 1 ,9167.431,244.404500,244.404500,244.404500
XS GIS Cut Line= 6
725909.905195891826722.072033615 725839.06226759826430.570299397
725838.631912526  826428.6171495725831.025530935826396.000855975
725786.308718694826230.602938903725767.932067634 826137.25951894
#Sta/Elev= 30
9699.013445.20279716.582446.49199726.873445.91339737.164443.37119757.747425.6577
 9788.62402.55489798.911 391.9799819.493374.84379840.075354.79939870.948322.7538
9901.822 297.5219912.113287.63539942.986263.06499953.277254.02349963.568249.7594
 9984.15 245.84510025.25245.355310035.53247.719610045.89252.107310056.25253.6956
10097.68254.6754 10118.4 257.08710128.76260.755910149.48 274.18710159.84279.4783
10190.91298.554110231.92321.493210242.11325.310210282.88336.081810300.96342.3023
#Mann= 3 , 0 , 0
9699.013    0.04       09699.013    0.04       010300.96    0.04       0
#XS Ineff= 2 , 0
       0                               0
Bank Sta=9699.013,10300.96
Exp/Cntr=0.3,0.1

Type RM Length L Ch R = 1 ,8923.026,244.404500,244.404500,244.404500
XS GIS Cut Line= 6
 726252.93196594826454.562755991726119.374731278826335.747515066
725955.934156294826256.323313437  725899.8692972826218.333719661
 725847.57450653826161.194812079725804.021607122826076.887002661
#Sta/Elev= 30
9699.057374.94459740.001367.95299754.021366.82429798.248 357.0669813.866352.0145
9829.483342.72499833.789342.21679845.464336.2332 9858.88335.32139862.467 333.029
9871.244324.49949907.006309.15599917.462303.67669929.973290.50829941.294281.2281
9963.371254.53459974.222246.05939985.074242.380910006.69240.648410017.45241.9218
10028.21246.654310039.19248.731910096.53256.020910117.18262.022510134.95272.0177
10177.81301.333910213.02323.183410229.79330.7568 10259.2340.385310300.86355.9611
#Mann= 3 , 0 , 0
9699.057   0.072       09699.057   0.072       010300.86   0.072       0
#XS Ineff= 2 , 0
       0                               0
Bank Sta=9699.057,10300.86
Exp/Cntr=0.3,0.1

Type RM Length L Ch R = 1 ,8678.622,244.404500,244.404500,244.404500
XS GIS Cut Line= 6
726361.258930208826285.620810964726294.794560345826217.534838071
726148.357197712826082.263875788726061.492654296  825995.0658731
726004.760626523  825926.2727889725954.380721672 825845.63722511
#Sta/Elev= 30
9699.021 331.4449727.838328.94269750.928322.86329807.503319.05839834.731314.6053
9871.592295.39459889.185289.03289902.799282.40019916.412270.16449930.542260.4152
9945.279251.86239957.253248.46389970.867246.4502 9984.48240.20399993.524237.7625
 10012.2236.436610018.23236.473610026.18 237.91710046.86248.973510075.18268.1461
10097.09286.829710116.62302.306110130.02309.653410156.57 322.75810194.73337.9034
10219.47349.172610240.89360.126410255.47366.091710267.03372.040710300.97387.0948
#Mann= 3 , 0 , 0
9699.021    0.06       09699.021    0.06       010300.97    0.06       0
#XS Ineff= 2 , 0
       0                               0
Bank Sta=9699.021,10300.97
Exp/Cntr=0.3,0.1

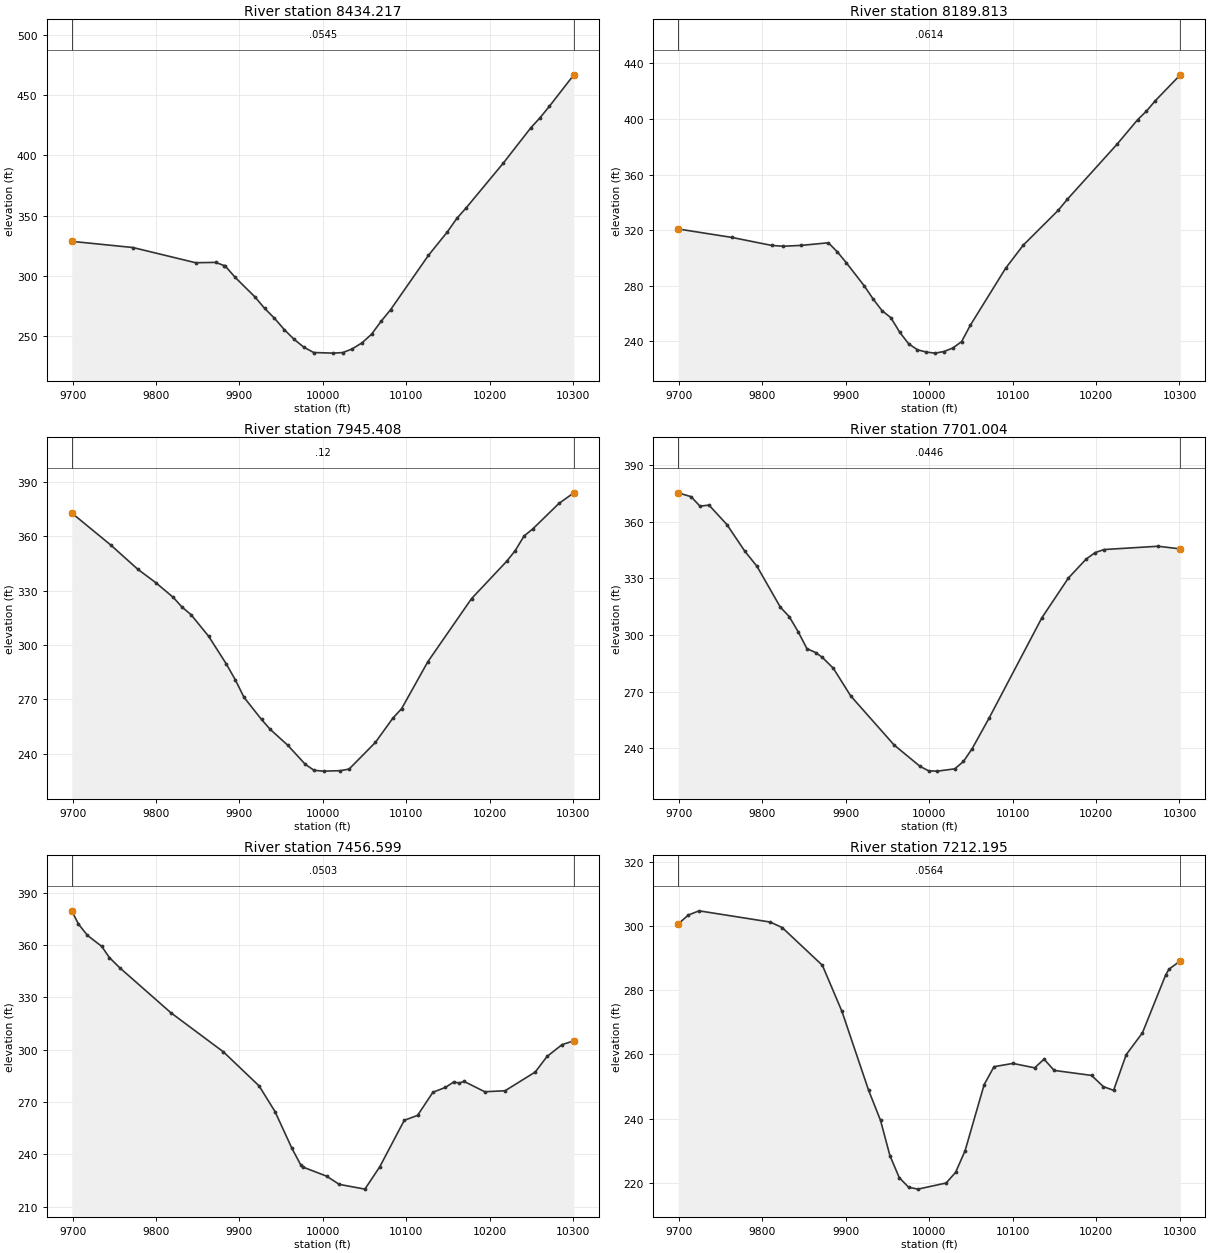
Type RM Length L Ch R = 1 ,8434.217,244.404600,244.404600,244.404600
XS GIS Cut Line= 6
726495.433262198826178.894848177726400.129569218826034.745939571
726333.298398082825926.533482309726311.714422277825889.909199376
726246.000833377825767.894278618726195.048970975825658.294789329
#Sta/Elev= 30
9699.008328.52949772.322323.40339847.533310.76849871.509311.04949881.576308.4435
9883.269307.85269895.022298.53949918.529282.45319930.282272.82569942.035264.6657
9953.789255.21479965.542247.15849977.296240.57339989.049236.172810012.39235.6665
   10024236.140710035.04239.118810047.09244.284210058.45251.3895 10069.8262.0644
10081.16 271.66210126.59316.871310149.31336.402810160.67347.611910172.03356.4912
10216.37393.537410249.46422.947310260.48431.267910271.51440.633910300.96466.8835
#Mann= 3 , 0 , 0
9699.008  0.0545       09699.008  0.0545       010300.96  0.0545       0
#XS Ineff= 2 , 0
       0                               0
Bank Sta=9699.008,10300.96
Exp/Cntr=0.3,0.1

Type RM Length L Ch R = 1 ,8189.813,244.404500,244.404500,244.404500
XS GIS Cut Line= 6
726671.802250318826109.771192234726624.217257291826006.427286415
726584.143113355 825906.96457193726557.500249314825832.621967305
 726552.22545182825817.300235569726460.585635749825546.595308047
#Sta/Elev= 30
9699.022320.82589763.105 314.7939810.924309.03499825.115308.42259846.677309.0507
9879.021310.91299889.802304.38169900.583 296.5249922.114279.89659932.737270.4234
 9943.36262.12559953.983257.00399964.606246.55329975.228238.28839985.851233.9546
9996.474232.297410007.06231.541510017.63232.701610028.19235.201410038.75239.8073
10049.31251.684310091.53292.564410112.65309.180910154.88334.443410165.44342.1408
10224.86 381.614 10249.9399.497810260.45405.638710271.01413.0979   10301431.7291
#Mann= 3 , 0 , 0
9699.022  0.0614       09699.022  0.0614       0   10301  0.0614       0
#XS Ineff= 2 , 0
       0                               0
Bank Sta=9699.022,10301
Exp/Cntr=0.3,0.1

Type RM Length L Ch R = 1 ,7945.408,244.404500,244.404500,244.404500
XS GIS Cut Line= 6
726889.013860419 826038.93627584726854.870381721825950.115909234
726818.800531292825846.964229682 726789.52556349825756.000902357
726788.927704344825754.092352006726698.526407535825468.040826865
#Sta/Elev= 30
9699.009372.86419746.079355.0661 9778.22341.78859799.585334.46719820.773 326.256
9831.367320.8486 9841.96316.77579863.148304.79719884.335289.49219894.929280.9125
9905.505271.11319926.516258.86899937.021253.38219958.031 244.6279979.041234.0827
9989.546230.7854   10001230.352910021.02230.593310031.51231.484510062.97246.1621
10083.95259.575710094.44264.8036 10125.9290.734910178.34325.607510220.29346.1162
10230.77352.128510241.26360.153710251.75 364.07210283.21378.1897   10301384.0044
#Mann= 3 , 0 , 0
9699.009    0.12       09699.009    0.12       0   10301    0.12       0
#XS Ineff= 2 , 0
       0                               0
Bank Sta=9699.009,10301
Exp/Cntr=0.3,0.1

Type RM Length L Ch R = 1 ,7701.004,244.404500,244.404500,244.404500
XS GIS Cut Line= 6
727119.668018782825969.289445307727084.715843679825880.786018164
 727058.99649653 825807.52387267 727003.81255932825614.292344079
726983.112569382825549.406597844726924.975751245825400.276904284
#Sta/Elev= 30
9699.015375.24279714.378373.2105 9725.13368.17469735.881368.75829757.385358.4325
9778.888344.31179793.396336.35559821.499314.67839832.097309.70739842.695301.7957
9853.294292.75759863.892290.66239871.816288.10749884.917282.39399905.839267.7066
9957.977241.68039989.079230.37629999.445228.019510009.81227.901610030.56229.1138
10040.94233.015210051.31 239.71910072.06256.265410135.03309.116810166.89330.1866
10188.19340.212110198.84343.589910209.54345.2164 10274.3346.959610300.98345.5592
#Mann= 3 , 0 , 0
9699.015  0.0446       09699.015  0.0446       010300.98  0.0446       0
#XS Ineff= 2 , 0
       0                               0
Bank Sta=9699.015,10300.98
Exp/Cntr=0.3,0.1

Type RM Length L Ch R = 1 ,7456.599,244.404500,244.404500,244.404500
XS GIS Cut Line= 6
727436.083134676825831.478130017 727391.10406214825769.580077609
727347.374399629825713.851780619727173.101316738825507.331314088
727121.747499036825437.965542688727067.127496785825356.539040785
#Sta/Elev= 30
9699.023379.62169707.031372.05919717.877365.52849734.888359.26299744.115352.8406
9756.477 347.0079817.824321.20499880.913298.7385 9923.63279.24249942.659264.5756
 9963.01 243.4289973.531233.96589976.137 232.72810004.45227.524910019.79 222.795
10050.47220.073110068.23232.837510097.66259.526310113.59262.341410131.96275.5814
10147.04278.414610156.85 281.47110163.85280.932310169.29281.853410194.17275.8937
10218.54276.478410254.66287.203510268.89296.142510286.84302.919810300.97305.0756
#Mann= 3 , 0 , 0
9699.023  0.0503       09699.023  0.0503       010300.97  0.0503       0
#XS Ineff= 2 , 0
       0                               0
Bank Sta=9699.023,10300.97
Exp/Cntr=0.3,0.1

Type RM Length L Ch R = 1 ,7212.195,244.404600,244.404600,244.404600
XS GIS Cut Line= 6
 727620.23447699825574.450790447727571.142668438825518.242120416
727505.852709675825463.330060834727265.886365767825322.927954356
727209.117045298825270.729304812727154.214851034825204.363375581
#Sta/Elev= 30
9699.077300.67959711.201303.44759724.028304.75479809.358301.2555 9823.76299.5249
9871.871287.77569895.341273.40239927.211248.87169941.604239.41839952.813228.4767
9964.021221.58999975.229218.59869986.438218.012810020.25219.921910031.58223.2487
10042.91229.9594 10065.8250.592410077.61256.171410100.25257.1941 10126.3255.8256
 10137.6 258.51510149.73255.015810194.51253.4569 10208.7249.964810220.97248.8077
10236.04259.905110255.52266.718210283.36284.754610287.48 286.60410300.94  289.15
#Mann= 3 , 0 , 0
9699.077  0.0564       09699.077  0.0564       010300.94  0.0564       0
#XS Ineff= 2 , 0
       0                10144.04       0
Bank Sta=9699.077,10300.94
Exp/Cntr=0.3,0.1

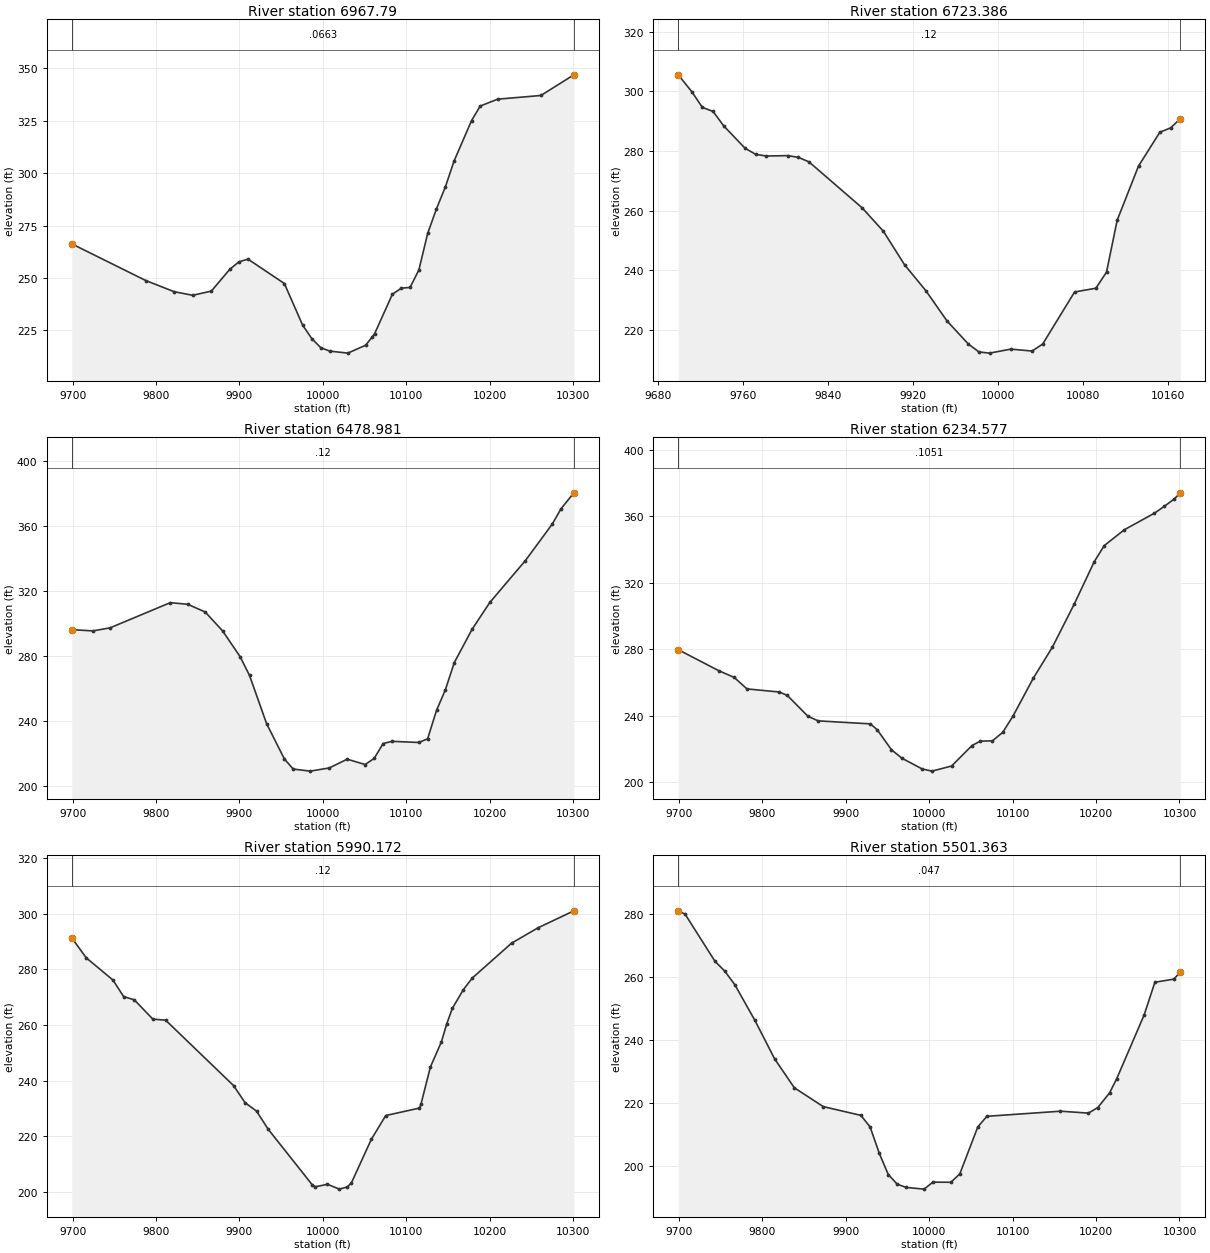
Type RM Length L Ch R = 1 , 6967.79,244.404500,244.404500,244.404500
XS GIS Cut Line= 6
727656.325459657825484.234121416727578.065018456825330.169469146
 727515.80607153825186.750857868727470.637264366825058.958204632
727451.461617002824994.676032234727433.827314039824926.759469825
#Sta/Elev= 30
9699.018266.23479787.889248.69269821.538243.4155 9843.97241.66179866.403243.6758
9888.388254.05049899.309257.61159910.231258.96169953.916247.28389975.759 227.461
 9986.68221.02649997.602216.625510008.44215.008610030.05214.0425 10051.4217.8273
10059.02221.671610062.07223.279810083.43242.156110094.07245.046710104.62245.4397
10115.17253.742110125.72271.186310136.26 282.96110146.81293.272110157.36305.7787
 10178.3325.069710188.74332.063810209.61335.339710261.48337.101310300.99346.9693
#Mann= 3 , 0 , 0
9699.018  0.0663       09699.018  0.0663       010300.99  0.0663       0
#XS Ineff= 2 , 0
       0                               0
Bank Sta=9699.018,10300.99
Exp/Cntr=0.3,0.1

Type RM Length L Ch R = 1 ,6723.386,244.404500,244.404500,244.404500
XS GIS Cut Line= 6
727777.070542338825527.557450437727770.820743403825475.791597745
727766.073583424825414.342670485727761.584899286 825185.90493906
727766.230232253 825112.20240057  727772.1913694 825055.86356615
#Sta/Elev= 30
9699.031305.5738 9711.68299.97599721.753294.67039731.825293.28839741.898288.4403
9761.997280.94689772.027278.91149782.056278.35779802.116278.48219812.146277.9085
 9822.15276.3867 9872.16260.99129892.164253.15129912.168241.87969932.172233.2222
9952.177223.02449972.181215.33849982.183 212.6689992.185212.270710012.19213.6115
10032.19212.973510042.19215.311810072.25232.774810092.29234.029410102.31239.4399
10112.33256.809310132.43274.991510152.55 286.349 10162.6287.775210171.79290.8679
#Mann= 3 , 0 , 0
9699.031    0.12       09699.031    0.12       010171.79    0.12       0
#XS Ineff= 2 , 0
       0                               0
Bank Sta=9699.031,10171.79
Exp/Cntr=0.3,0.1

Type RM Length L Ch R = 1 ,6478.981,244.404500,244.404500,244.404500
XS GIS Cut Line= 6
727912.792775226825549.582378349727940.124158305825439.151860458
727969.510845547825344.263963535727988.755073674825291.227637489
728029.017574714825191.482978572728107.013631223824980.572276024
#Sta/Elev= 30
9699.038296.24799724.362295.46589744.965297.35669817.146312.87579838.084311.8761
9859.021307.11639879.958295.42799900.895279.57159912.134268.03399932.627238.2976
9953.903216.56729964.541210.29849984.899209.025510007.74 210.97910029.27216.3915
 10050.8213.094610061.57216.863410072.33226.010810083.03227.400210115.02226.6821
10125.68 228.94710136.34246.4354   10147259.220610157.67275.968310178.99296.4466
10200.31313.054110242.96338.854910274.95361.209810285.61370.754110300.99380.5844
#Mann= 3 , 0 , 0
9699.038    0.12       09699.038    0.12       010300.99    0.12       0
#XS Ineff= 2 , 0
       0                               0
Bank Sta=9699.038,10300.99
Exp/Cntr=0.3,0.1

Type RM Length L Ch R = 1 ,6234.577,244.404500,244.404500,244.404500
XS GIS Cut Line= 6
728050.201270809825615.159706405 728110.61807203 825518.79058365
728210.618898025825384.679434207728234.675653139825345.579747451
728317.146213735825229.343858778728390.612457551825119.144379514
#Sta/Elev= 30
9699.029279.74719747.713267.08699766.168263.05419781.436256.17179820.305254.2912
9829.791 252.2529854.548239.7187 9866.75236.96149929.457235.14799937.772231.5201
 9954.58219.63339967.141 214.5289991.488208.048110003.18206.746510026.73209.8113
10051.25222.127510061.14224.774910075.77224.959310088.03230.036510100.29239.7514
10124.82 262.68910147.55281.203310173.76307.107510197.79332.629610209.81342.3034
10233.85 351.81810269.91361.764110281.92365.936710293.94  370.4510300.98374.0153
#Mann= 3 , 0 , 0
9699.029  0.1051       09699.029  0.1051       010300.98  0.1051       0
#XS Ineff= 2 , 0
       0                               0
Bank Sta=9699.029,10300.98
Exp/Cntr=0.3,0.1

Type RM Length L Ch R = 1 ,5990.172,488.809100,488.809100,488.809100
XS GIS Cut Line= 6
728184.217525529825773.581697763728243.611572992825699.241906871
728302.237004464825632.004299388728413.753065518825519.930482077
728456.110371633825474.033626244728582.157715111825322.643541349
#Sta/Elev= 30
9699.022291.32659716.297284.16619748.406276.15469761.206270.21849774.005269.0488
9796.288262.10629811.504261.75739893.035238.24339906.816232.10139920.597229.0686
9934.378222.62849987.561202.51729991.138201.904610005.57202.782310019.91201.0534
10029.31201.838610034.25203.272310058.11218.906710075.45227.490110115.87 230.166
10117.65 231.53410129.03244.950710142.19253.949510148.42260.277110155.35 266.023
10168.51272.694110179.18276.873210226.38289.416810258.02294.919310300.99301.0229
#Mann= 3 , 0 , 0
9699.022    0.12       09699.022    0.12       010300.99    0.12       0
#XS Ineff= 2 , 0
       0                               0
Bank Sta=9699.022,10300.99
Exp/Cntr=0.3,0.1

Type RM Length L Ch R = 1 ,5501.363,244.404500,244.404500,244.404500
XS GIS Cut Line= 6
728498.141952253825969.221276629728607.674041657825897.893968704
728663.113232493825865.602944243728704.568981273825846.214463602
728865.085374837 825781.63710802729031.720895209825694.113237586
#Sta/Elev= 30
9699.035 280.9679707.219279.92749743.019 264.9679754.953261.77019766.886257.5004
9790.753246.2636 9814.62233.94079838.222224.7635 9872.94218.77989918.064215.9973
9929.104212.2961 9940.13203.91619950.847 197.2169961.564194.14359972.282193.1199
9993.716192.573110004.44194.789410025.89194.749710036.62197.415810058.16212.3184
10069.05215.703910157.31217.324610190.83216.721510202.01 218.47810216.17223.1305
10224.82227.700610257.65247.915210270.48258.278510293.31259.282910300.98261.5295
#Mann= 3 , 0 , 0
9699.035   0.047       09699.035   0.047       010300.98   0.047       0
#XS Ineff= 2 , 0
       0                               0
Bank Sta=9699.035,10300.98
Exp/Cntr=0.3,0.1