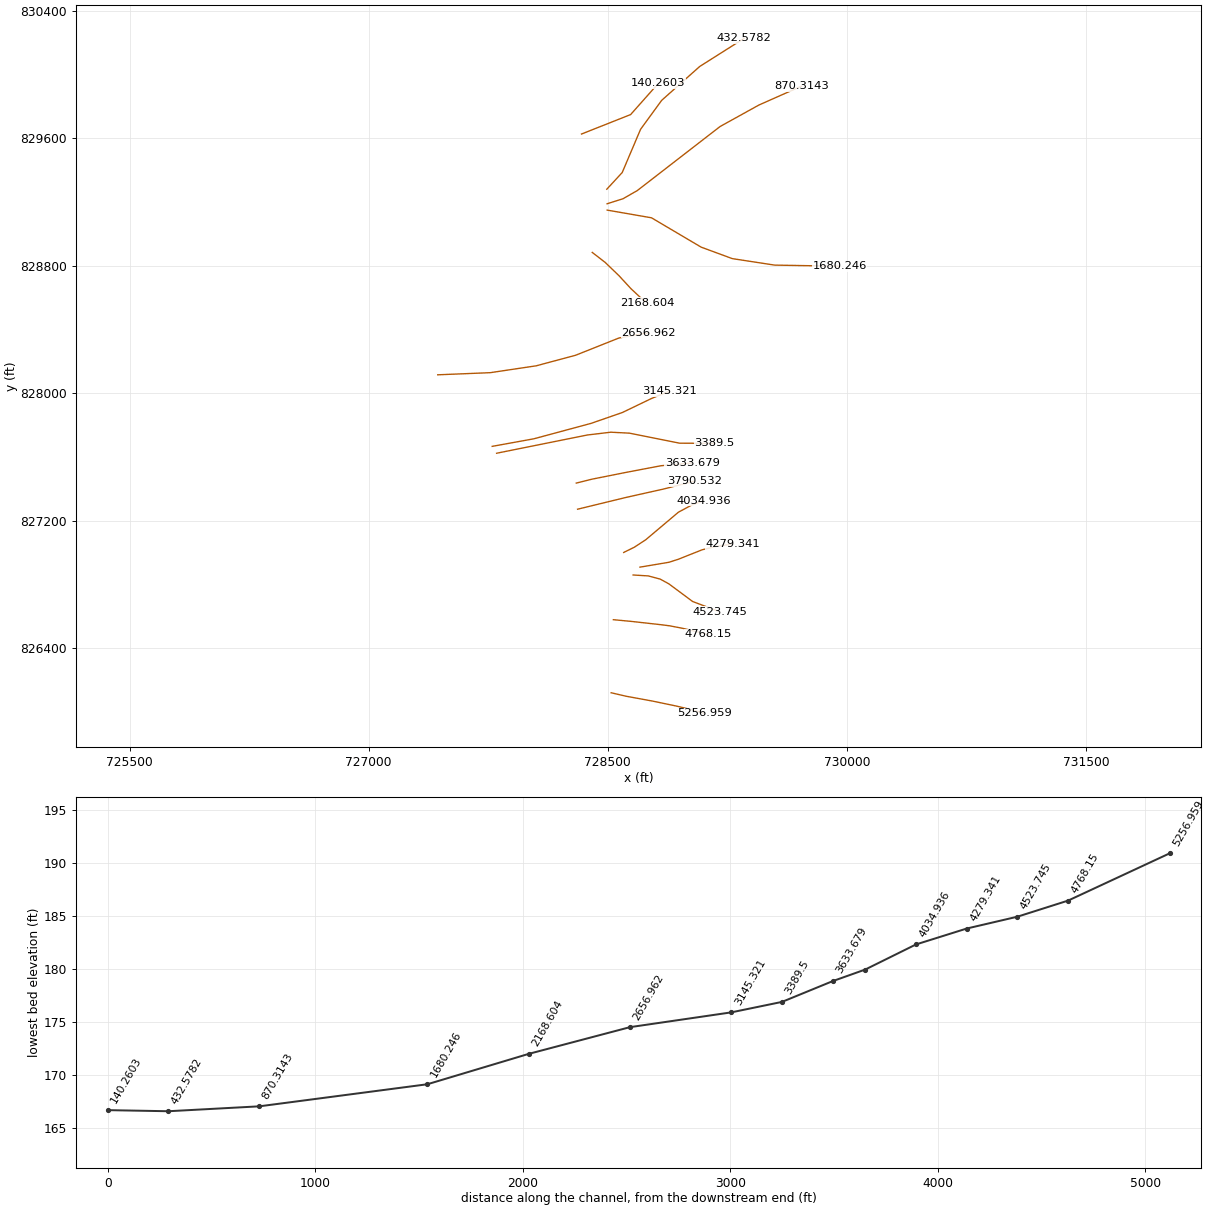
HEC-RAS study 14876_ras.prj: 14876

--- 14876_ras.g01 (geometry) --- (continued)

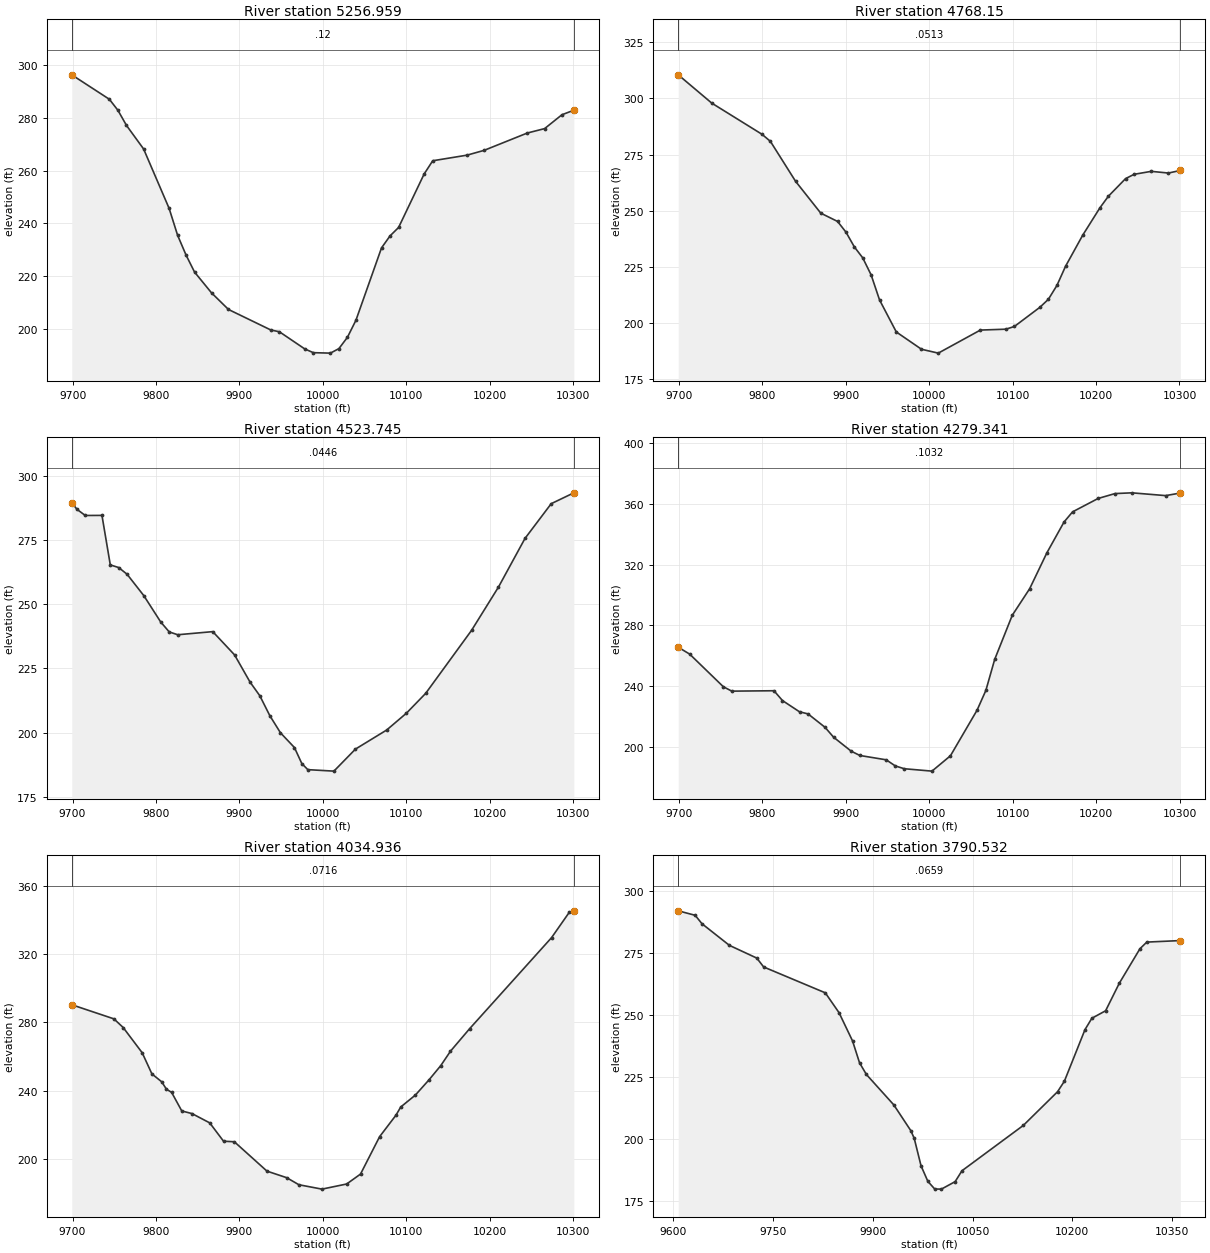
Type RM Length L Ch R = 1 ,5256.959,488.809000,488.809000,488.809000
XS GIS Cut Line= 6
728521.102284959826121.648345154728613.780638918826100.113737908
728785.289969241826068.563191522 728933.05794838826037.638767559
729026.357280424826015.351167122729108.760577849825992.388133052
#Sta/Elev= 30
9699.017296.22999744.085286.98619754.351282.81469764.617 277.087 9785.15268.1757
 9815.74245.69659825.908 235.5249836.076228.01459846.244221.59249866.579213.7383
9886.915207.45269937.754199.68179947.922199.02499978.458192.5074 9988.66191.1065
10009.08190.9358 10019.3 192.63810029.52196.919410039.74203.3863 10070.4230.7553
10080.62235.293210090.85238.472310121.52258.7259 10131.8263.717210172.93265.8378
10193.49267.663410245.18274.208810265.94275.8787 10286.7 281.12410300.99282.8417
#Mann= 3 , 0 , 0
9699.017    0.12       09699.017    0.12       010300.99    0.12       0
#XS Ineff= 2 , 0
       0                               0
Bank Sta=9699.017,10300.99
Exp/Cntr=0.3,0.1

Type RM Length L Ch R = 1 , 4768.15,244.404600,244.404600,244.404600
XS GIS Cut Line= 6
728534.953892281826580.037029752728648.221095618826569.261432385
728835.278670354826548.408156459728888.778229134826541.567024439
728971.814767119826525.446023145729128.861529338826487.974481517
#Sta/Elev= 30
9699.005310.51969739.232297.90619799.503284.00269809.548280.84289839.729263.0435
9869.915  248.879890.039245.17029900.101240.41439910.163233.82339920.225 228.938
9930.287221.34249940.349210.20429960.473  195.919990.659188.2048 10010.8186.4815
10061.27196.756710091.83197.151110102.02198.354510132.58206.9028 10142.8210.4721
10153.08216.676110163.36225.173510183.92239.018510204.48251.185110214.76256.4139
10235.32264.2514 10245.6266.180510266.17267.499210286.73266.741610300.98267.8965
#Mann= 3 , 0 , 0
9699.005  0.0513       09699.005  0.0513       010300.98  0.0513       0
#XS Ineff= 2 , 0
       0                               0
Bank Sta=9699.005,10300.98
Exp/Cntr=0.3,0.1

Type RM Length L Ch R = 1 ,4523.745,244.404500,244.404500,244.404500
XS GIS Cut Line= 6
728658.824240265826860.435161037728753.712334414826854.687787949
728828.548653589826834.633703532728882.828169077826805.089807211
729031.902802055826694.230456121729201.003602537826630.326820618
#Sta/Elev= 30
9699.115289.71139705.292287.10429715.295284.68889735.301284.71959745.304265.4067
9755.328264.38279765.383261.77719785.495253.40959805.768 243.1279815.968239.2584
9826.167238.16619868.132239.37599894.271 230.3019912.784219.71619924.549214.3522
9936.534206.58799949.314199.90369966.022 194.1659974.874187.91769982.081185.5359
10013.37184.960810039.18193.5562 10076.6200.999810100.21207.5442 10123.3215.2767
 10178.4239.897810210.63256.776910242.39275.732510273.83289.289710300.96293.5246
#Mann= 3 , 0 , 0
9699.115  0.0446       09699.115  0.0446       010300.96  0.0446       0
#XS Ineff= 2 , 0
       0                               0
Bank Sta=9699.115,10300.96
Exp/Cntr=0.3,0.1

Type RM Length L Ch R = 1 ,4279.341,244.404500,244.404500,244.404500
XS GIS Cut Line= 6
 728701.44953063826909.712608154728883.195713989826940.168411223
728941.921330141826958.945029141729092.034317267827018.674379296
729180.993458302827039.694069151729282.408028114827055.010791156
#Sta/Elev= 30
9699.075265.53219712.769261.02559753.191239.46669763.297 236.5919813.835236.8549
9824.039230.37539844.447222.96729854.651221.5949 9875.06212.73219885.317 206.207
9906.315 197.0299916.813194.15899948.403   191.39959.205187.29039970.007 185.424
10003.26183.842610025.38193.9665 10057.3224.031810067.85237.083310078.41257.5114
10099.51 286.64710120.33304.1248   10141327.827610161.56 348.14510171.79354.8261
10202.42363.661910222.64366.878210242.87367.373110283.32365.537710300.93367.2225
#Mann= 3 , 0 , 0
9699.075  0.1032       09699.075  0.1032       010300.93  0.1032       0
#XS Ineff= 2 , 0
       0                               0
Bank Sta=9699.075,10300.93
Exp/Cntr=0.3,0.1

Type RM Length L Ch R = 1 ,4034.936,244.404500,244.404500,244.404500
XS GIS Cut Line= 6
728599.706332347827001.887434482728666.660069733827034.887755823
728738.083492303827081.624761609728942.925464355 827254.37462532
729024.627104253827298.124466608729100.312206084827326.309278661
#Sta/Elev= 30
9699.068290.36749749.565282.10179760.714277.01469783.457262.26379795.141249.8431
9806.824 245.2459812.604240.86139818.759239.03789830.957228.13269843.156226.6079
9864.435221.15959881.003210.41199893.941210.0957 9933.08192.88319956.726189.0389
9971.362184.9062    9999182.3409 10028.6185.343210045.21191.158510068.11213.0734
10087.79225.712710093.41230.445610110.97237.4388 10127.4246.410510141.45254.7236
10153.08263.1652   10176276.326110274.22 329.67210295.34344.429710300.95345.3928
#Mann= 3 , 0 , 0
9699.068  0.0716       09699.068  0.0716       010300.95  0.0716       0
#XS Ineff= 2 , 0
       0                               0
Bank Sta=9699.068,10300.95
Exp/Cntr=0.3,0.1

Type RM Length L Ch R = 1 ,3790.532,156.852600,156.852600,156.852600
XS GIS Cut Line= 5
728310.304389179 827273.11716862728358.828810513827284.915465772
728612.303318739827346.563484401728848.414429903827399.341262221
729043.810756683827448.839645192
#Sta/Elev= 30
9607.859291.94259633.274290.14589643.566 286.7429684.732278.04819725.898272.9252
9736.189269.35559828.813258.94919849.396250.9838 9869.73239.6018 9880.27230.7834
9890.562226.09559931.671213.88329957.335203.48179962.411200.39619972.658189.3472
9982.905183.09789993.152180.030310003.18179.973510023.89182.993510034.14187.3633
10126.36205.621310177.71219.150110188.02223.400310218.97244.156810229.29248.7223
10249.92251.729410270.55262.8314 10301.5276.681410311.81279.363910362.17279.9758
#Mann= 3 , 0 , 0
9607.859  0.0659       09607.859  0.0659       010362.17  0.0659       0
#XS Ineff= 2 , 0
       0                               0
Bank Sta=9607.859,10362.17
Exp/Cntr=0.3,0.1

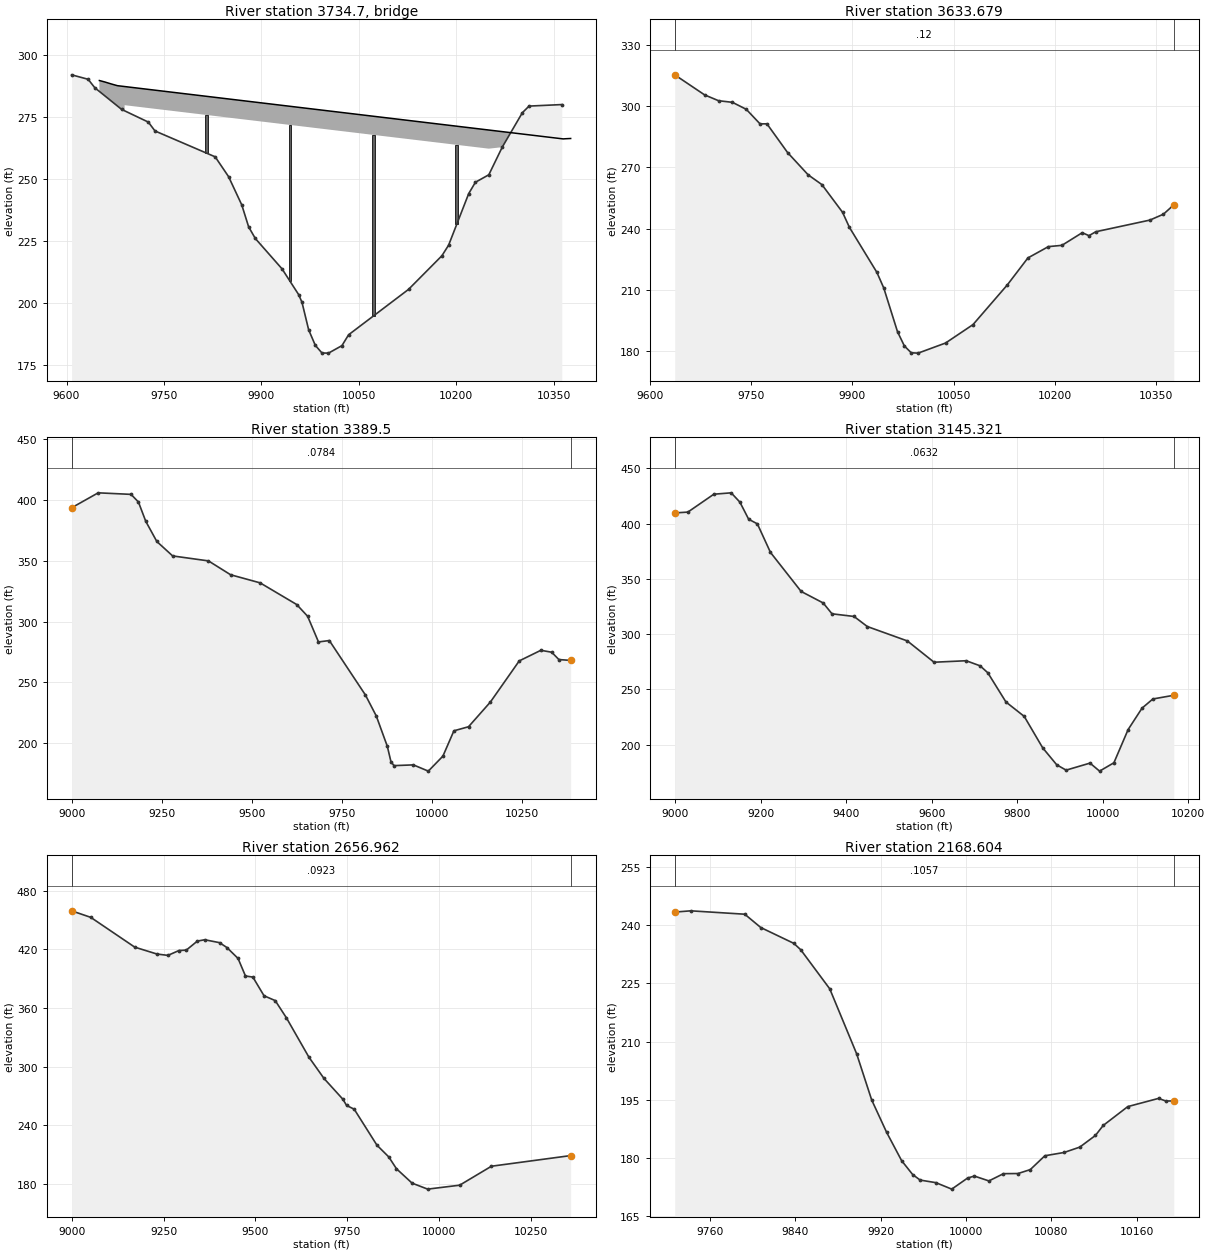
Type RM Length L Ch R = 3 ,  3734.7,,,
BEGIN DESCRIPTION:
END DESCRIPTION:
Bridge Culvert--1,0,-1,-1, 0
Deck Dist Width WeirC Skew NumUp NumDn MinLoCord MaxHiCord MaxSubmerge Is_Ogee
58.249150,40.354300,2.6,0, 13, 13, , , 0.95, 0, 0,0,,
 9650.59 9658.88 9660.14 9669.16 9678.27 9689.43 9689.4310326.9010326.9010364.37
10368.6410369.7910375.86
  289.65  289.07  288.97  288.25  287.58  287.23  287.23  267.33  267.33  266.16
  266.24  266.25  266.33
 -710.35 -710.93 -711.03 -711.75 -712.42 -712.77  279.73  259.83 -732.67 -733.84
 -733.76 -733.75 -733.67
 9650.59 9658.88 9660.14 9669.16 9678.27 9695.37 9695.3710332.8310332.8310364.37
10368.6410369.7910375.86
  289.65  289.07  288.97  288.25  287.58  287.05  287.05  267.14  267.14  266.16
  266.24  266.25  266.33
 -710.35 -710.93 -711.03 -711.75 -712.42 -712.95  279.55  259.64 -732.86 -733.84
 -733.76 -733.75 -733.67
Pier Skew, UpSta & Num, DnSta & Num=  ,9815.72, 2 ,9821.66, 2 , 0 , 0 , 0 ,,
    4.00    4.00
 -716.71  283.29
    4.00    4.00
 -716.90  283.10
Pier Skew, UpSta & Num, DnSta & Num=  ,9944.02, 2 ,9949.95, 2 , 0 , 0 , 0 ,,
    4.00    4.00
 -720.72  279.28
    4.00    4.00
 -720.90  279.10
Pier Skew, UpSta & Num, DnSta & Num=  ,10072.31, 2 ,10078.24, 2 , 0 , 0 , 0 ,,
    4.00    4.00
 -724.72  275.28
    4.00    4.00
 -724.91  275.09
Pier Skew, UpSta & Num, DnSta & Num=  ,10200.60, 2 ,10206.54, 2 , 0 , 0 , 0 ,,
    4.00    4.00
 -728.73  271.27
    4.00    4.00
 -728.91  271.09
BR Coef=-1 , 0 , 0 ,, 0 ,,,0.8,0,1,0,
WSPro=,,,, 1 ,,,, 0 ,,,, 0 ,,,,-1 ,-1 ,-1 , 0 , 0 , 0 , 0 , 0
BC Design=,, 0 ,, 0 ,,,,,,

Type RM Length L Ch R = 1 ,3633.679,244.179200,244.179200,244.179200
XS GIS Cut Line= 5
728301.935841829827436.955556348728399.192701161827461.166034073
 728602.35242337827501.756311834728834.019090027827545.922978505
729030.269089997 827563.42297852
#Sta/Elev= 30
9636.432315.4734 9680.81305.6096 9701.42302.76839722.031301.97429742.579298.5407
9762.974291.39319773.171291.43089803.764277.34589834.357266.38189854.753261.5828
9885.345248.01529895.543240.60939936.334218.49739946.527210.81869966.887189.3807
9977.067182.39569987.247179.04629997.427178.879610038.15183.835510078.87192.8781
10129.77212.364110160.31225.6001 10190.7231.156110210.77231.783410240.89237.9876
10250.93236.533110260.97238.451810341.29244.179410361.37247.0707 10376.7251.6521
#Mann= 3 , 0 , 0
9636.432    0.12       09636.432    0.12       0 10376.7    0.12       0
#XS Ineff= 2 , 0
       0                               0
Bank Sta=9636.432,10376.7
Exp/Cntr=0.3,0.1

Type RM Length L Ch R = 1 ,  3389.5,244.179100,244.179100,244.179100
XS GIS Cut Line= 6
727802.282945254 827624.10380908728371.355948397827738.628271324
728518.871271144827756.105577117728635.330264641827750.218598506
728950.966539211827687.192426932729167.641067133827686.285920276
#Sta/Elev= 30
8999.133393.69389072.901 406.0069164.109404.73579184.548398.46699204.988382.5424
9235.648365.95069279.561354.06739378.951349.97259440.449338.56569522.339331.8986
9623.968314.04519654.266 304.3789684.381283.26539714.496284.41479814.663239.5889
9844.826222.31559875.392197.39139885.582184.65879893.927181.44499947.728 182.062
9989.241176.9205 10029.8189.284510060.26210.105410100.88213.457210161.49233.7678
10241.63267.657510301.64276.381810331.65 274.80810351.66268.763510384.35268.0618
#Mann= 3 , 0 , 0
8999.133  0.0784       08999.133  0.0784       010384.35  0.0784       0
#XS Ineff= 2 , 0
       0                               0
Bank Sta=8999.133,10384.35
Exp/Cntr=0.3,0.1

Type RM Length L Ch R = 1 ,3145.321,488.358300,488.358300,488.358300
XS GIS Cut Line= 6
727774.634165803827667.361607703728036.377747685827714.854850245
 728395.38038685827811.646245911728591.859779647827879.873929187
728775.973087399827968.571730572728884.222649116828011.726014062
#Sta/Elev= 30
8999.079409.58289029.789410.33759090.469426.51689131.081427.77119151.496419.3227
9171.912403.89469192.327399.68149222.949373.85699294.687338.52949346.221328.1082
9366.835318.2916 9418.37315.89769449.412306.7761 9543.04293.74679605.458274.4799
9680.571275.82919713.152271.23459731.228264.93079773.641238.48799816.401225.4579
9859.518197.02699892.403 181.6539914.327176.82119970.208183.19359992.611175.9326
10026.13183.502710059.33213.535310091.92232.939310117.21241.221210166.12244.5709
#Mann= 3 , 0 , 0
8999.079  0.0632       08999.079  0.0632       010166.12  0.0632       0
#XS Ineff= 2 , 0
       0                               0
Bank Sta=8999.079,10166.12
Exp/Cntr=0.3,0.1

Type RM Length L Ch R = 1 ,2656.962,488.358300,488.358300,488.358300
XS GIS Cut Line= 6
 727432.90106446828116.182522308727762.736339173828129.590976829
728051.085782464 828172.64705947728297.565842102828238.687204874
728570.532279474828347.336081847728755.789674878828379.632971603
#Sta/Elev= 30
8999.071459.4068 9051.17452.73069171.212422.19819231.344415.21219261.429413.7939
9291.515418.76019311.571419.19699341.695428.43339361.814429.79849402.091426.8317
9422.279421.8042 9452.56410.68749472.747392.71019492.934391.57979523.394372.4521
9553.872367.51019584.351349.88779645.567309.66619686.636287.88589737.973266.6517
9748.325260.20719769.095256.33139831.058 219.4929863.147207.5412 9884.23195.3858
9926.737180.67659969.244174.537110056.44178.564210143.02197.979210358.85208.8658
#Mann= 3 , 0 , 0
8999.071  0.0923       08999.071  0.0923       010358.85  0.0923       0
#XS Ineff= 2 , 0
       0                               0
Bank Sta=8999.071,10358.85
Exp/Cntr=0.3,0.1

Type RM Length L Ch R = 1 ,2168.604,488.358200,488.358200,488.358200
XS GIS Cut Line= 6
728402.500141312828883.839622012728483.978643003828820.764963327
728570.281053092828737.662660137728645.068309534828656.524682866
728704.039181176828601.659226983728746.517341749 828568.62879449
#Sta/Elev= 30
 9727.05243.34069742.146243.66139792.663242.79149807.687239.35889838.646235.2855
9845.123233.63849872.316223.57489897.513206.85379911.565195.00049925.617186.6302
9939.669179.3392 9949.98175.77649956.976174.34729971.803173.6752 9986.63172.0132
10001.48174.8639 10007.8175.377810021.45174.1241 10035.1175.992910048.76176.0293
10060.23177.041510073.89180.604710091.93181.450310106.61182.830710121.29185.8347
10128.53188.3979 10151.6193.260710180.38195.368610187.18194.7102 10194.7194.7049
#Mann= 3 , 0 , 0
 9727.05  0.1057       0 9727.05  0.1057       0 10194.7  0.1057       0
#XS Ineff= 2 , 0
       0                               0
Bank Sta=9727.05,10194.7
Exp/Cntr=0.3,0.1

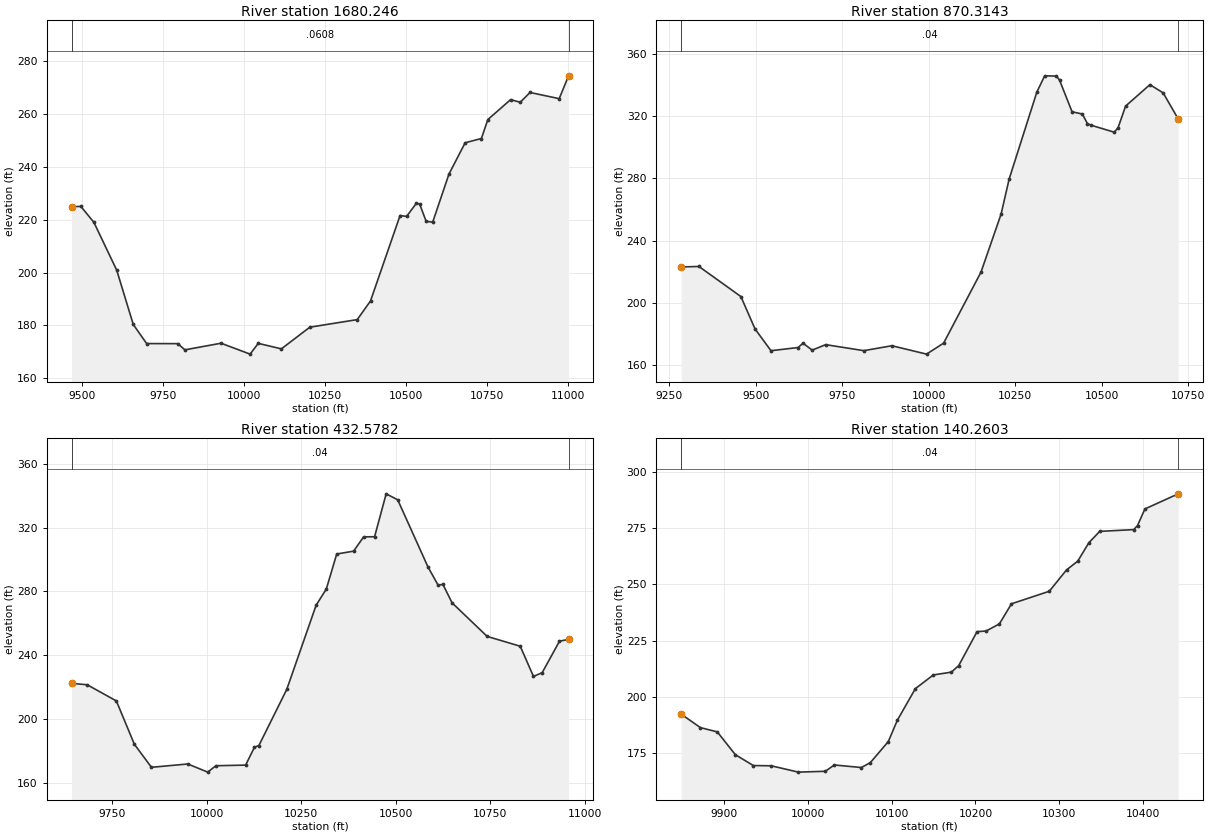
Type RM Length L Ch R = 1 ,1680.246,809.931500,809.931500,809.931500
XS GIS Cut Line= 6
728496.156588718829149.312177398728773.987107828829101.103204164
729085.662974593828916.899741757 729281.02867116828844.961722297
729546.435470547828804.279453667729953.874430371828797.414848405
#Sta/Elev= 30
9467.692224.88719496.549224.97499536.617218.98569607.103200.88419658.217 180.347
9699.473173.1391  9795.6173.10679817.344170.75999928.937173.271410018.57169.1461
10043.62 173.21510115.06171.135310202.75179.329110349.03182.194710389.98189.2458
10481.15221.5426 10501.3221.204710531.53226.166210541.61225.8724 10561.7219.3155
10581.78219.028910631.89237.179510681.97249.042810732.01250.654410752.02257.8238
10822.03265.333510852.03264.365110882.03268.054510972.04 265.71611000.92274.3468
#Mann= 3 , 0 , 0
9467.692  0.0608       09467.692  0.0608       011000.92  0.0608       0
#XS Ineff= 2 , 0
       0                               0
Bank Sta=9467.692,11000.92
Exp/Cntr=0.3,0.1

Type RM Length L Ch R = 1 ,870.3143,437.736100,437.736100,437.736100
XS GIS Cut Line= 6
728495.433521248829189.080888225728595.030823722829220.539960924
728685.605396939829272.378344819729203.921582918829673.417542785
729447.662557135829808.436537322729715.129307948829926.881369205
#Sta/Elev= 30
9285.015223.1143  9336.4223.3962 9457.47204.08389498.332  183.269544.438169.2631
9622.934171.30639636.989174.11039663.494169.62419702.365173.15919812.864169.2917
9893.851172.45249994.099167.0629 10043.3174.1341 10151.3219.747710209.41257.0744
10232.66279.572910312.83335.550810335.42 345.953 10369.3345.801310378.35343.1737
10414.48322.858410444.23321.395710458.97315.213410470.02314.172110536.29309.7171
10547.34312.513210569.22326.493510639.45340.278310677.78334.986110721.35318.1707
#Mann= 3 , 0 , 0
9285.015    0.04       09285.015    0.04       010721.35    0.04       0
#XS Ineff= 2 , 0
       0                               0
Bank Sta=9285.015,10721.35
Exp/Cntr=0.3,0.1

Type RM Length L Ch R = 1 ,432.5782,292.317900,292.317900,292.317900
XS GIS Cut Line= 6
728493.773681352829280.372082395728590.297310674829385.032316442
728705.508911709829656.279695031728837.780384449829837.772226252
729076.602770505830050.460526478 729355.55897937830226.830138312
#Sta/Elev= 30
 9642.45222.28329683.872221.39599761.025211.25659808.678184.05949853.839169.6278
9949.903 171.708 10002.6166.599910024.23170.608110102.85171.008510126.11182.2113
 10137.9183.291610211.69218.538210289.24 271.29610316.11281.406710343.69303.4104
10388.27305.185810414.79314.142910443.83314.248110474.41341.148210504.98337.3841
10584.97295.281510611.74 283.88510624.41284.353110648.85272.732210741.47251.7206
10828.92245.552610863.96226.607210887.11 229.03710932.68248.7146 10956.7249.8472
#Mann= 3 , 0 , 0
 9642.45    0.04       0 9642.45    0.04       0 10956.7    0.04       0
#XS Ineff= 2 , 0
       0                               0
Bank Sta=9642.45,10956.7
Exp/Cntr=0.3,0.1

Type RM Length L Ch R = 1 ,140.2603,0.000000,0.000000,0.000000
XS GIS Cut Line= 3
728334.890969455829626.539277151728643.145173818  829748.6399685
728817.288782746829944.801734895
#Sta/Elev= 30
9848.479192.41459871.454186.4425 9891.62184.54869913.132174.45469934.644 169.622
9956.156169.50979988.424166.703410020.69167.079910031.45169.880310063.72168.7456
10074.47170.921310095.98180.282810106.74189.732510128.25203.732710149.76209.8161
10171.27 211.04410180.04213.948610201.91228.991410212.95229.307810228.66232.4648
10243.08241.364410288.27246.922610308.89  256.4110322.26260.270110335.63268.4849
10348.52273.485910389.12274.269910393.71276.078110402.49283.430210442.34290.1398
#Mann= 3 , 0 , 0
9848.479    0.04       09848.479    0.04       010442.34    0.04       0
#XS Ineff= 2 , 0
       0                               0
Bank Sta=9848.479,10442.34
Exp/Cntr=0.3,0.1